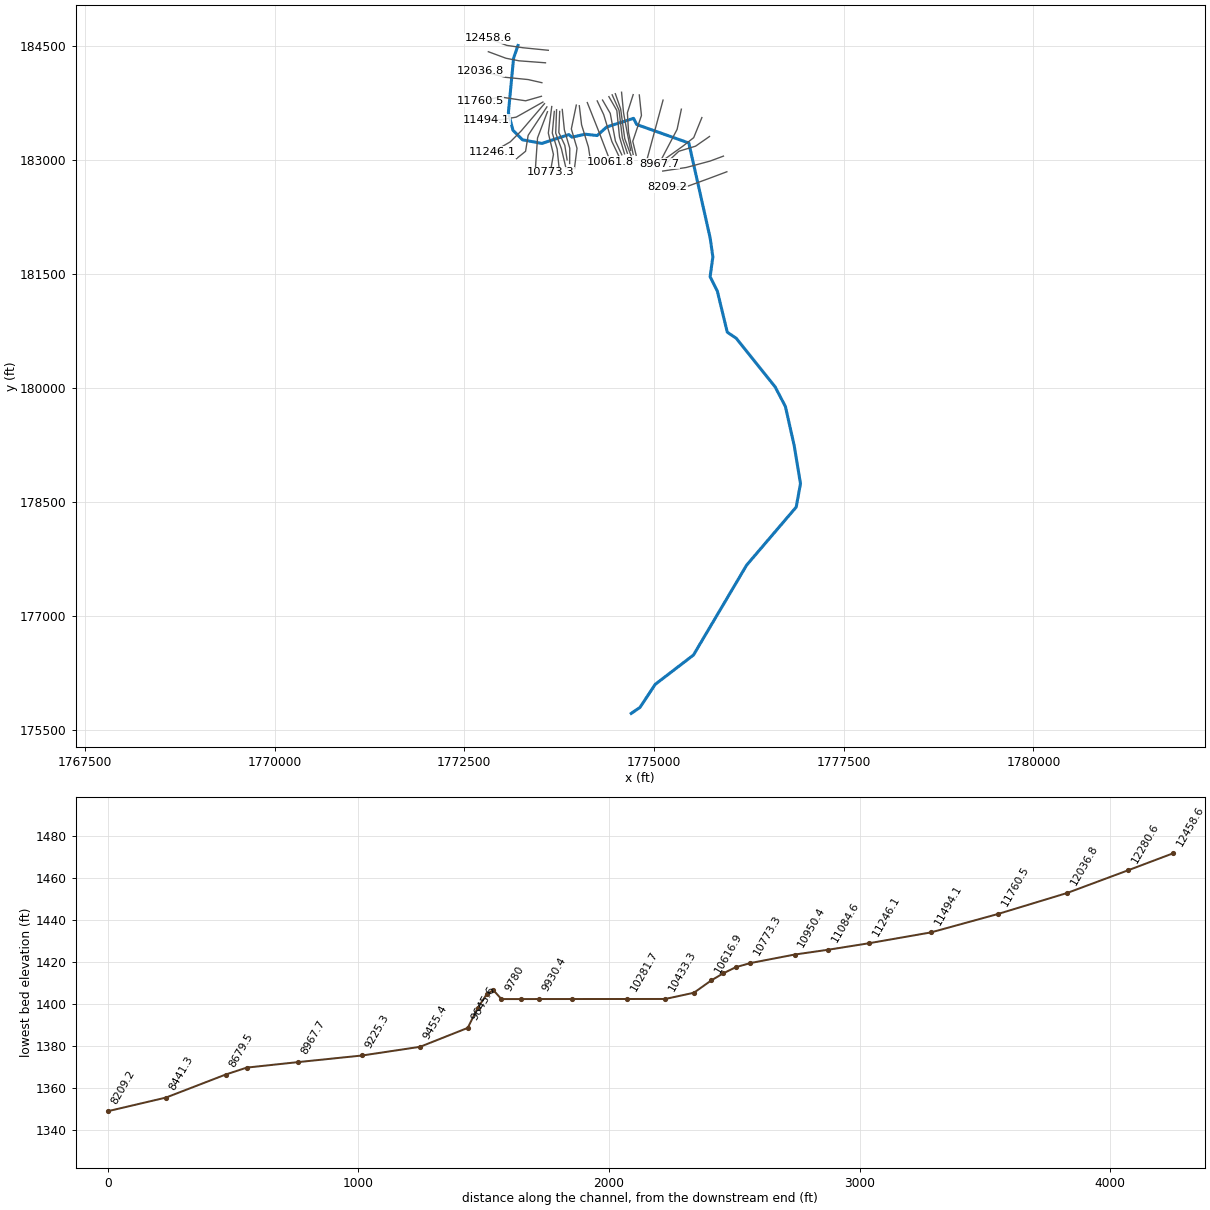
--- Twin Branch.prj (project) ---

Proj Title=Twin Branch
Current Plan=p01
Default Exp/Contr=0,0
English Units
Geom File=g01
Flow File=f01
Plan File=p01
BEGIN DESCRIPTION:
END DESCRIPTION:
DSS Export Rating Curves= 0
DSS Export Rating Curve Sorted= 0
DSS Export Volume Flow Curves= 0
DXF OffsetX= 0
DXF OffsetY= 0
DXF ScaleX= 0
DXF ScaleY= 0

--- Twin Branch.p01 (plan) ---

Plan Title=Floodplain
Program Version=4.00
Geom File=g01
Flow File=f01
K Sum by GR=0
Std Step Tol=0.01
Critical Tol=0.01
Num of Std Step Trials=20
Max Error Tol=0.3
Flow Tol Ratio=0.001
Split Flow NTrial=30
Split Flow Tol=0.02
Split Flow Ratio=0.02
Log Output Level=0
Friction Slope Method=1
Unsteady Friction Slope Method=2
Unsteady Bridges Friction Slope Method=1
Global Log Level=0
CheckData=False
Run HTab=0
Run UNet=0
Run PostProcess=0
UNET Theta=0
UNET Theta Warmup=0
UNET ZTol=0
UNET ZSATol=0
UNET MxIter=0
UNET MaxInSteps=0
UNET DtIC=0
UNET DtMin=0
UNET MaxCRTS=0
UNET WFStab=0
UNET SFStab=0
UNET WFX=0
UNET SFX=0
UNET DSS MLevel=0
UNET DZMax Abort=0
UNET Convert EG Bridges=0
UNET Use Existing IB Tables=0
UNET Froude Limit=0
UNET Froude Power=0
Write IC File=0
Echo Input=False
Echo Output=False
Write Detailed=0

--- Twin Branch.f01 (steady flow) ---

Flow Title=NFF Regression Equation
Program Version=4.00
Number of Profiles=1
Profile Names=P100yr
River Rch & RM=Twin Branch,Main      ,12458.6
615.2798
River Rch & RM=Twin Branch,Main      ,10433.3
648.9697
Boundary for River Rch & Prof#=Twin Branch,Main      ,1
Up Type=0
Dn Type=3
Dn Slope=0.017666

--- Twin Branch.g01 (geometry) ---

Geom Title=USGS 10m DEM
Program Version=4.00

River Reach=Twin Branch     ,Main
Reach XY= 30
     1773207.815      184512.232     1773149.748      184344.863
     1773081.721      183628.055     1773141.427      183397.282
     1773266.205      183271.161     1773522.471       183222.86
     1773877.353      183338.917     1773920.287      183305.375
     1774092.026      183344.284     1774251.689      183326.842
     1774376.468      183439.545     1774730.134      183553.203
      1774773.42      183471.441     1775459.315      183228.393
     1775740.984      181974.401     1775775.868      181728.198
     1775739.642      181468.578     1775834.903      181278.055
      1775965.72      180737.348      1776083.79      180657.516
     1776595.651      180018.863     1776731.834      179759.243
     1776848.563      179240.003     1776930.407        178742.9
     1776874.055      178434.308     1776221.129      177670.231
     1775520.273      176486.149     1775016.462      176100.409
     1774815.206      175796.512     1774700.457      175718.123

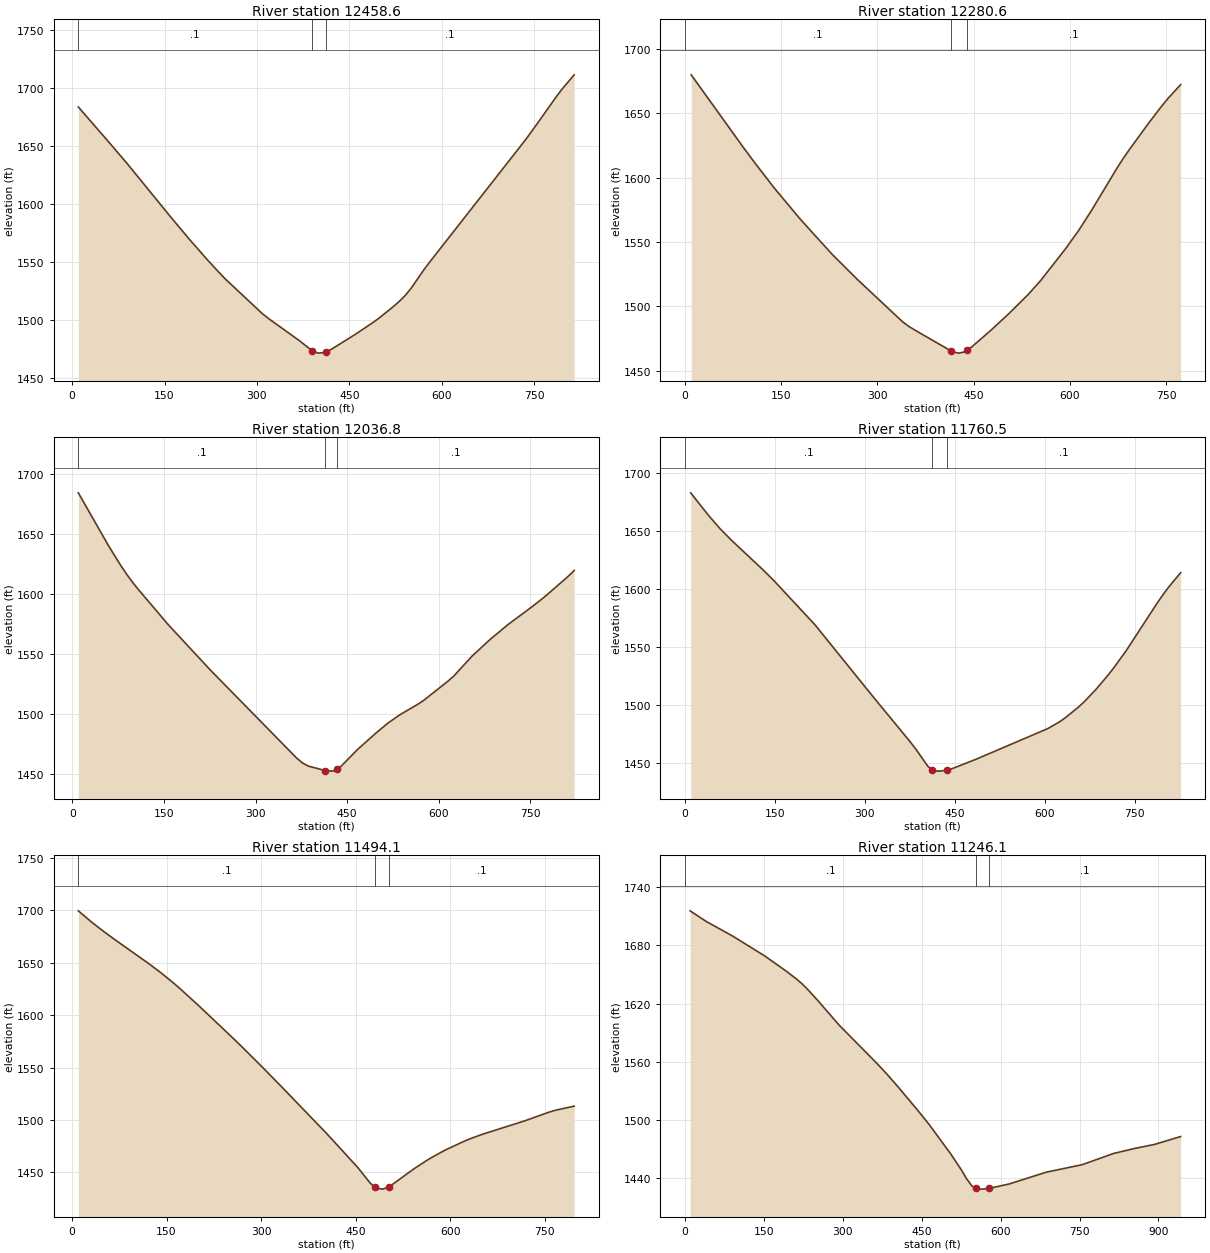
Type RM Length L Ch R = 1 ,12458.6 ,179.3,178,176.8
XS GIS Cut Line= 4
     1773607.739       184449.33       1773270.6      184483.044
     1773060.934      184513.759     1772813.588      184606.661
#Sta/Elev= 30
      10 1683.44    59.8 1653.04    89.7 1634.46   159.4 1589.08   189.3 1570.14
   219.2 1552.07   239.2 1540.54   249.1 1535.12   308.9 1505.43   318.9 1501.26
   369.1 1482.16   389.3 1473.71   399.4 1471.53   409.5 1472.01   411.9 1472.59
   419.5 1474.41   459.9 1487.78   490.2 1498.55   500.3 1502.58   520.5 1511.21
   530.5 1515.83   540.6  1521.1   550.7 1527.71   570.3 1542.81   580.1 1549.74
   736.7 1655.72   756.2 1670.02   785.6 1692.09   795.4 1698.92   814.9 1711.13
#Mann= 3 , 0 , 0
      10      .1       0   389.3    .045       0   411.9      .1       0
Bank Sta=389.3,411.9
XS Rating Curve= 0 ,0
Exp/Cntr=0.3,0.1

Type RM Length L Ch R = 1 ,12280.6 ,241.1,243.7,246.4
XS GIS Cut Line= 4
     1773570.279      184284.506     1773221.902      184310.728
     1773049.586      184344.442     1772817.334        184430.6
#Sta/Elev= 30
      10 1679.99    89.8 1624.52   109.8 1611.08   139.7  1591.8   179.7 1567.89
   229.6 1540.38   269.5  1520.6   339.4 1487.91   349.4 1484.21   359.1 1481.29
   414.9 1465.22   417.6 1464.49   427.4 1463.53   437.2 1464.65   439.9 1465.65
   446.9 1468.23   476.2 1480.94   505.4 1494.41   534.9 1509.03   554.7 1520.06
   594.3  1545.3   614.1 1559.16   633.9 1574.55   673.6 1607.48   683.5 1615.16
   693.4 1622.24   723.1 1642.56   742.9 1655.47   752.8  1661.5   772.7 1672.36
#Mann= 3 , 0 , 0
       0      .1       0   414.9    .045       0   439.9      .1       0
Bank Sta=414.9,439.9
XS Rating Curve= 0 ,0
Exp/Cntr=0.3,0.1

Type RM Length L Ch R = 1 ,12036.8 ,278,276.4,274.7
XS GIS Cut Line= 4
     1773522.768      184022.614     1773341.023      184063.938
     1773042.094       184093.46     1772717.788      184176.225
#Sta/Elev= 30
     9.8 1684.23    58.9 1640.53    78.5 1624.39    88.3 1616.97    98.1 1610.14
   107.9 1603.92     157 1574.57   226.4 1536.56   366.6 1463.92   376.6 1459.54
   386.6 1456.88   414.2  1453.2   426.7 1452.73  433.74 1454.43   436.7 1455.13
   466.7 1470.64   496.6 1484.21   516.3 1492.55     536 1499.55   565.5 1508.32
   575.4 1511.68   614.7 1527.47   624.6  1531.9   654.1 1548.26   683.6 1562.12
   713.2 1574.65   752.6 1589.49   772.2 1597.32   811.6 1614.68   821.5 1619.64
#Mann= 3 , 0 , 0
     9.8      .1       0   414.2    .045       0  433.74      .1       0
Bank Sta=414.2,433.74
XS Rating Curve= 0 ,0
Exp/Cntr=0.3,0.1

Type RM Length L Ch R = 1 ,11760.5 ,257.5,266.4,275.3
XS GIS Cut Line= 4
       1773516.8      183843.604     1773308.689      183784.088
     1772974.666      183834.987     1772708.701      183778.797
#Sta/Elev= 30
     9.8 1682.86    39.4 1663.48      59 1651.78    78.7 1641.46   127.9 1617.63
   147.6 1607.59   216.5 1569.27   315.8 1505.62   375.5 1468.09   385.4 1461.46
   405.3  1446.7   412.6 1443.91   415.2 1442.91   425.1 1442.74   437.6 1443.64
     445 1444.76   484.8 1452.88   604.7 1479.39   624.8 1485.36   634.9 1489.14
     655 1497.57   665.1 1502.35   685.2 1513.29   705.4 1525.62   715.4  1532.3
   735.6 1546.74   785.9 1586.75     796 1594.36     806 1601.34   826.2 1613.94
#Mann= 3 , 0 , 0
       0      .1       0   412.6    .045       0   437.6      .1       0
Bank Sta=412.6,437.6
XS Rating Curve= 0 ,0
Exp/Cntr=0.3,0.1

Type RM Length L Ch R = 1 ,11494.1 ,231,248,265.1
XS GIS Cut Line= 4
     1773536.565      183767.559     1773184.442      183569.021
      1772989.65      183535.307     1772794.858      183535.307
#Sta/Elev= 30
    10.1 1699.56    30.3 1689.25    50.5 1679.79    70.7 1670.92   121.3 1649.45
   141.5 1640.28   161.7 1630.39   171.8 1625.11   202.1 1608.51   262.8 1573.88
   303.2 1549.71   333.5 1531.12   404.2 1486.99   453.7 1454.47   473.4 1439.55
   480.7 1436.12   483.3 1434.89   493.2 1434.02   503.1 1436.15   542.6 1453.44
   562.4 1461.23   572.3 1464.78     592 1471.26   621.4 1479.48   631.1 1481.94
   650.6 1486.25   718.8 1499.26   757.8 1507.65   767.5 1509.36   796.7 1513.19
#Mann= 3 , 0 , 0
    10.1      .1       0   480.7    .045       0   503.1      .1       0
Bank Sta=480.7,503.1
XS Rating Curve= 0 ,0
Exp/Cntr=0.3,0.1

Type RM Length L Ch R = 1 ,11246.1 ,144.2,161.5,178.8
XS GIS Cut Line= 4
     1773557.319      183746.543     1773248.124      183385.467
     1773105.776       183243.12     1772875.709      183110.683
#Sta/Elev= 30
    10.1 1715.67    40.5 1704.79      91 1689.63   151.7 1669.26   192.2 1653.72
   212.4 1645.34   222.5 1640.58   232.6 1635.18   252.9 1623.16   293.3 1597.86
   364.1 1558.96   384.3 1547.25   404.6 1534.63     445 1508.53   465.3 1494.73
   505.6 1464.88   525.7 1448.53   535.8 1439.26   545.8    1432   553.5 1429.81
   555.9 1429.13     566 1428.86   578.5 1429.63   616.3 1434.16   686.5 1446.28
   755.3 1454.09   814.3 1465.54   853.7 1470.65     893    1475   942.1 1483.04
#Mann= 3 , 0 , 0
       0      .1       0   553.5    .045       0   578.5      .1       0
Bank Sta=553.5,578.5
XS Rating Curve= 0 ,0
Exp/Cntr=0.3,0.1

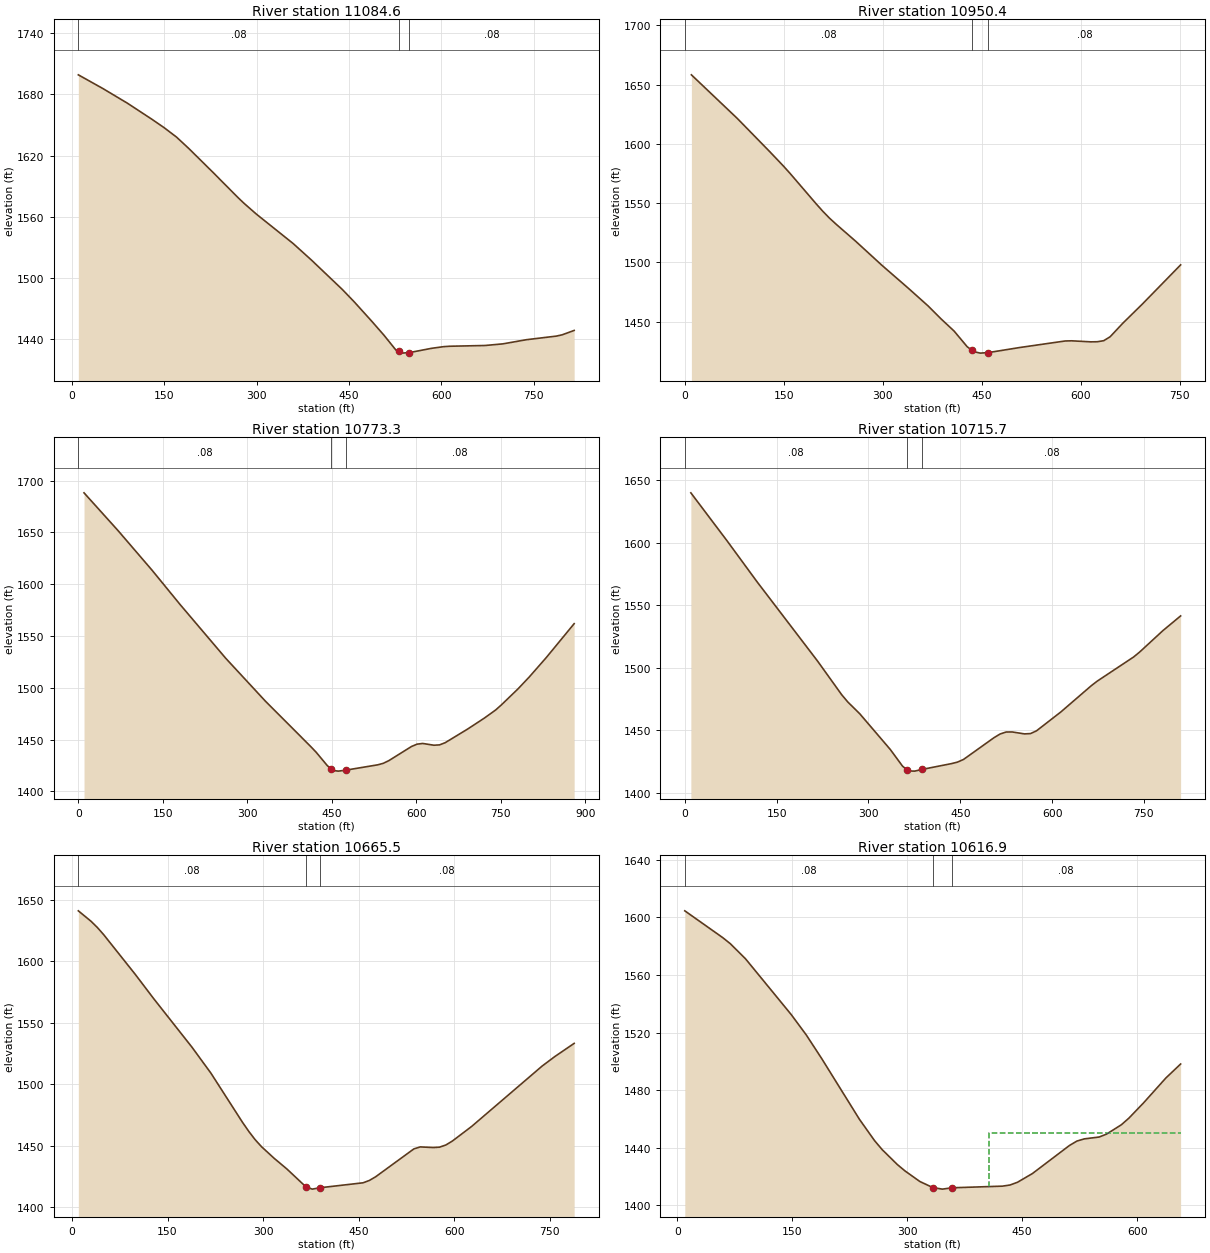
Type RM Length L Ch R = 1 ,11084.6 ,131.8,134.2,136.7
XS GIS Cut Line= 4
     1773589.009      183703.877     1773341.773      183329.278
      1773308.06      183119.502     1773188.188      183022.106
#Sta/Elev= 30
      10 1699.31    49.9 1685.83    89.8 1671.41   129.7 1655.58   149.6  1647.3
   169.6 1638.11   189.5 1626.93   229.4  1603.1   269.3 1578.78   279.3 1573.03
   299.2 1562.49   359.1 1533.51     389 1517.17   438.9 1488.43   458.5 1476.11
   487.5  1456.7   506.8 1443.34   526.1 1428.82  530.66 1427.54   535.8 1425.79
   548.2 1426.32     584 1430.51   603.4 1432.13     613 1432.54     671 1433.29
   699.9 1434.89   738.5    1439   786.8 1442.51   796.4  1443.8   815.8  1448.1
#Mann= 3 , 0 , 0
      10     .08       0  530.66    .045       0   548.2     .08       0
Bank Sta=530.66,548.2
XS Rating Curve= 0 ,0
Exp/Cntr=0.3,0.1

Type RM Length L Ch R = 1 ,10950.4 ,168.6,177,185.4
XS GIS Cut Line= 4
     1773596.501      183640.195     1773465.391      183295.564
     1773450.407      183078.296     1773439.169      182913.472
#Sta/Elev= 30
      10  1658.3    79.7 1621.45   129.6 1593.01   149.5 1581.35   159.5 1575.19
   199.3 1549.37   209.3 1543.15   219.2 1537.48   229.2 1532.37   259.1 1517.88
     299 1497.53   338.8  1478.3   368.7  1463.4   388.5 1452.39   408.3 1442.09
   428.1 1428.92   435.4 1425.86     438 1424.78   447.9  1423.5   460.4 1423.97
   507.3 1428.19   576.6 1433.74   586.5 1433.89   615.7 1433.01   625.4 1433.11
   635.1 1433.99   644.8 1437.29   664.3 1448.86   693.4 1464.73   751.7 1497.95
#Mann= 3 , 0 , 0
       0     .08       0   435.4    .045       0   460.4     .08       0
Bank Sta=435.4,460.4
XS Rating Curve= 0 ,0
Exp/Cntr=0.3,0.1

Type RM Length L Ch R = 1 ,10773.3 ,56,57.6,59.2
XS GIS Cut Line= 4
     1773652.801      183708.497     1773607.739      183359.246
     1773675.167      183078.296     1773633.982      182842.912
#Sta/Elev= 30
    10.1 1688.32    70.4 1651.88   130.8 1613.59   181.1  1580.1   261.6 1528.48
     332 1487.06   411.9 1443.51   421.9 1437.82   441.8 1424.83   449.2 1421.29
   451.8 1420.05   461.7 1419.45   474.2 1420.35   531.5 1425.55   541.4 1427.01
   551.4 1429.69   591.3 1443.24   601.2 1445.51   611.2 1446.18   631.1 1444.48
   641.1 1444.82     651 1446.89   690.9 1460.07   720.7 1470.71   740.6 1478.49
   750.6 1483.31   780.5 1498.99   800.4 1510.45   830.3 1529.02     880 1561.91
#Mann= 3 , 0 , 0
       0     .08       0   449.2    .045       0   474.2     .08       0
Bank Sta=449.2,474.2
XS Rating Curve= 0 ,0
Exp/Cntr=0.3,0.1

Type RM Length L Ch R = 1 ,10715.7 ,48.6,50.3,51.9
XS GIS Cut Line= 5
     1773686.405      183643.941     1773660.183      183359.246
     1773723.865       183149.47     1773746.341      182932.202
     1773753.833      182846.044
#Sta/Elev= 30
     9.9 1639.85      69 1601.54   118.3 1568.62   216.9 1505.44   256.3 1478.57
   266.2 1472.81   285.9 1463.31   335.7 1434.82   355.7  1421.5   363.1  1418.6
   365.6 1417.62   375.6 1417.52   388.1 1418.94   435.4 1423.49   445.3  1424.7
   455.3 1426.84   505.1 1444.23   515.1 1447.18     525 1448.77   534.9 1448.81
   554.8 1447.27   564.7  1447.5   574.6 1449.72   614.3 1464.78     664 1485.73
   673.9 1489.46   733.2  1508.7   742.8 1512.54   781.2 1529.83     810 1541.52
#Mann= 3 , 0 , 0
       0     .08       0   363.1    .045       0   388.1     .08       0
Bank Sta=363.1,388.1
XS Rating Curve= 0 ,0
Exp/Cntr=0.3,0.1

Type RM Length L Ch R = 1 ,10665.5 ,46.1,48.6,51.1
XS GIS Cut Line= 4
     1773716.373      183666.417     1773705.135      183359.246
     1773780.055      183153.216      1773839.99      182898.488
#Sta/Elev= 30
     9.9 1640.99    29.7 1632.56    39.7 1627.48    49.6 1621.66    99.2 1589.36
   128.9 1569.09   188.4 1530.01   218.1 1508.91   267.7 1468.91   277.6  1461.5
   287.5 1454.83   297.5 1449.12   317.3 1439.69   337.3 1431.01   367.2 1416.46
   377.1 1414.61   389.6 1415.75   456.9 1419.75   466.8 1421.66   476.8 1424.71
   536.7 1447.34   546.7 1448.95   566.9 1448.44   576.9 1448.73     587 1450.55
   597.1 1453.72   627.3 1465.57     738 1514.71   758.1  1522.5   788.3 1533.17
#Mann= 3 , 0 , 0
     9.9     .08       0   367.2    .045       0   389.6     .08       0
Bank Sta=367.2,389.6
XS Rating Curve= 0 ,0
Exp/Cntr=0.3,0.1

Type RM Length L Ch R = 1 ,10616.9 ,73.1,68.9,64.8
XS GIS Cut Line= 4
     1773757.579      183643.941     1773746.341      183366.738
     1773825.007      183198.168     1773854.974      183007.122
#Sta/Elev= 30
     9.9 1604.62    59.4 1585.99    69.4 1581.73    89.2 1571.23   148.6 1532.61
   168.4 1518.36   188.3 1502.11   237.8 1459.69   257.6 1444.82   267.5  1438.6
   287.2 1428.28     297 1423.92   316.6 1416.48   333.5 1412.27     346 1411.19
   358.5 1412.12   424.3 1413.26   434.1 1414.04   443.9 1415.94   463.5 1422.04
   511.8 1441.54   521.5 1444.59   531.1 1446.11   550.5  1447.4   560.1 1449.42
   579.5 1455.93   589.2 1460.47   608.5 1471.17   637.5  1488.4   656.8 1498.15
#Mann= 3 , 0 , 0
     9.9     .08       0   333.5    .045       0   358.5     .08       0
#XS Ineff= 2 , 0
                          406.82         1450.42
Permanent Ineff=
       F       F
Bank Sta=333.5,358.5
XS Rating Curve= 0 ,0
Exp/Cntr=0.3,0.1

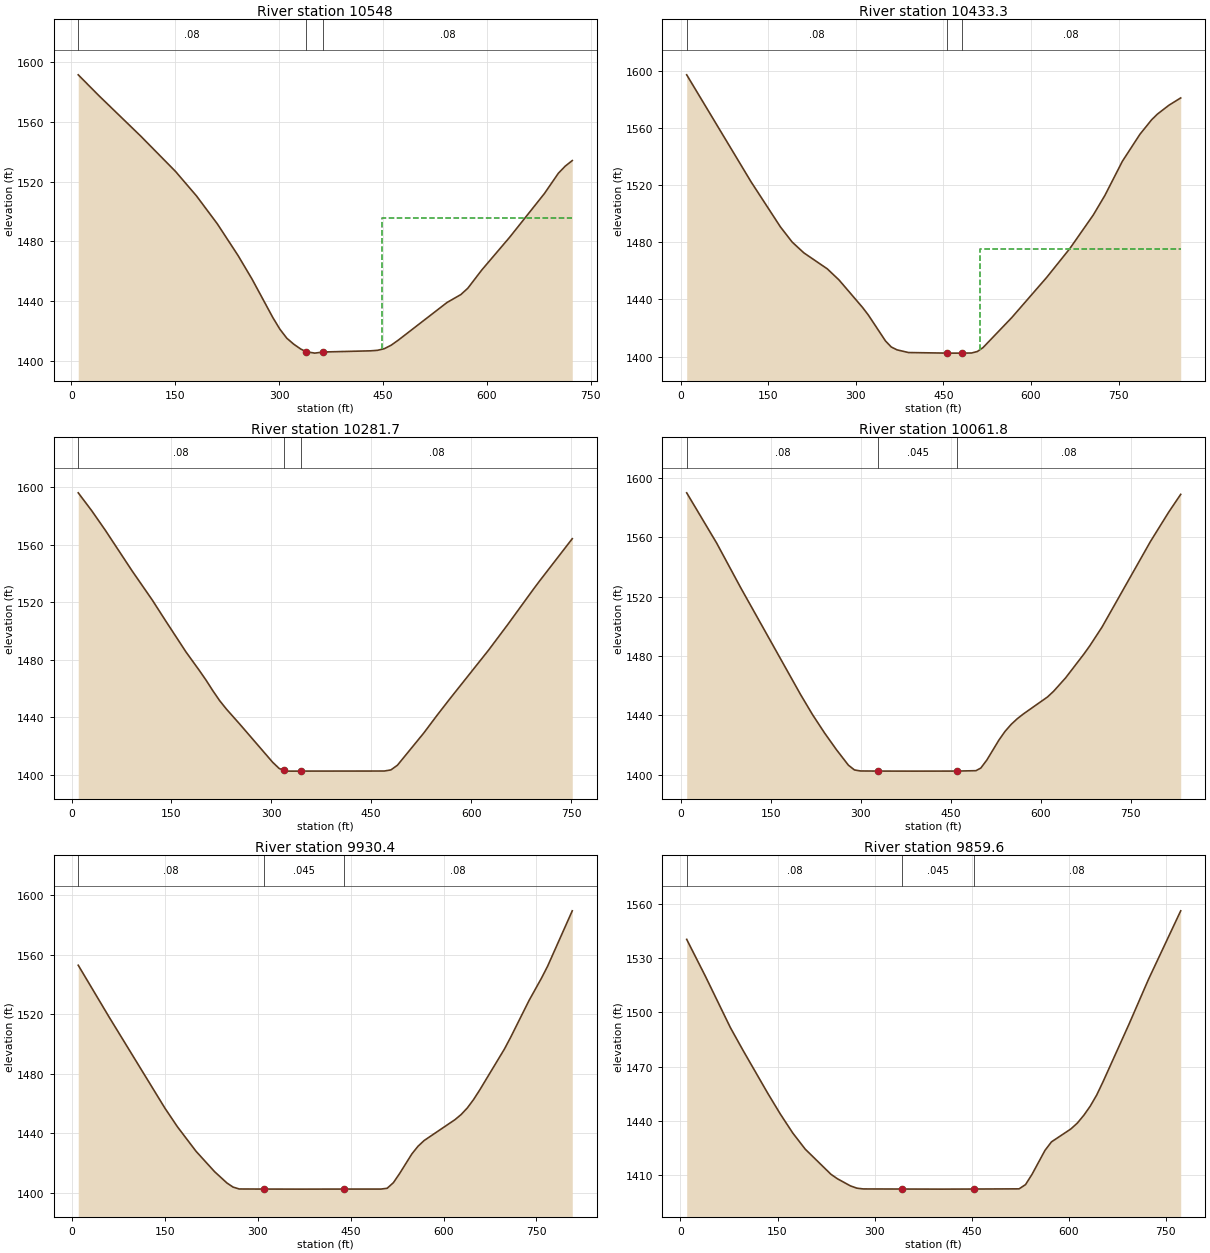
Type RM Length L Ch R = 1 ,10548   ,115.3,114.6,113.1
XS GIS Cut Line= 4
     1773791.293      183670.163     1773819.344       183400.61
     1773890.433      183159.413     1773888.688      182958.424
#Sta/Elev= 30
      10  1591.3    40.1 1577.26   100.4 1550.29   150.6  1526.7   180.7 1510.44
   210.8 1491.79   240.9 1470.51     261 1454.83   291.1 1429.08   301.2 1421.37
   311.2 1415.33   321.3  1411.3   331.4 1408.07     339 1406.34   351.5 1405.35
     364  1406.1   431.9 1406.88     442 1407.22   452.1 1408.32   462.1  1410.7
   472.2 1414.01   542.6 1439.17   562.7 1444.51   572.7 1448.74   592.8 1460.89
     633 1482.73   683.3 1511.99   703.4 1525.52   713.4 1530.31   723.5    1534
#Mann= 3 , 0 , 0
      10     .08       0     339    .045       0     364     .08       0
#XS Ineff= 2 , 0
                          448.41         1495.94
Permanent Ineff=
       F       F
Bank Sta=339,364
XS Rating Curve= 0 ,0
Exp/Cntr=0.3,0.1

Type RM Length L Ch R = 1 ,10433.3 ,150.7,151.6,152.5
XS GIS Cut Line= 4
     1773976.281      183727.777     1773910.934      183413.259
     1773985.854      183158.531     1773951.593       182890.83
#Sta/Elev= 30
      10 1597.33   120.5 1522.27   170.7 1490.77   190.7 1480.21   210.8 1472.62
     251 1461.41     271 1453.66   311.2 1434.47   321.2 1429.14   350.7 1410.91
   360.6 1406.68   370.4 1404.69   390.1  1402.8   456.2  1402.4   468.7 1402.39
   481.2  1402.4   498.2 1402.48   508.1 1403.53   517.9  1406.3   567.1 1427.29
   626.7 1455.32   666.7 1475.71   706.7 1499.11   726.7 1512.88   756.7 1536.83
   786.7 1555.68   806.7 1565.82   816.7 1569.83   836.6 1576.09   856.6 1581.15
#Mann= 3 , 0 , 0
      10     .08       0   456.2    .045       0   481.2     .08       0
#XS Ineff= 2 , 0
                           512.1         1475.28
Permanent Ineff=
       F       F
Bank Sta=456.2,481.2
XS Rating Curve= 0 ,0
Exp/Cntr=0.3,0.1

Type RM Length L Ch R = 1 ,10281.7 ,214.3,219.9,221
XS GIS Cut Line= 4
     1774016.052      183718.861      1774046.02      183467.879
     1774135.924      183175.692     1774165.892      182984.646
#Sta/Elev= 30
    10.1 1596.09    30.3 1583.67    50.6 1570.16      91 1541.75   121.3 1521.46
   141.5 1506.88   171.9 1485.32   192.1 1472.35   202.2 1465.59   212.3 1458.29
   222.4 1451.46   232.5 1445.61   252.8 1435.01   302.1 1408.52   311.9  1404.2
   319.2 1402.88   321.8  1402.4   331.7 1402.38   344.2  1402.4   469.7 1402.45
   479.6 1403.23   489.4  1406.5   528.9 1428.89   548.6 1441.06   568.1 1452.71
   626.2 1486.58   655.2 1504.52   693.8 1529.15   703.5 1535.14   751.9 1564.16
#Mann= 3 , 0 , 0
    10.1     .08       0   319.2    .045       0   344.2     .08       0
Bank Sta=319.2,344.2
XS Rating Curve= 0 ,0
Exp/Cntr=0.3,0.1

Type RM Length L Ch R = 1 ,10061.8 ,133.6,131.4,132
XS GIS Cut Line= 3
     1774121.298      183760.665     1774276.315      183371.086
     1774424.366      182984.646
#Sta/Elev= 30
      10 1590.08    59.9  1556.2    99.8 1526.22   199.7 1454.05   219.6 1440.52
   239.6 1428.18   259.6 1416.78   279.5 1406.35   289.5 1403.18   299.5 1402.48
   329.4  1402.4   389.3 1402.37   459.7  1402.4  491.91 1402.67     500 1404.43
   510.1 1409.86   530.3 1423.37   540.4 1429.17   550.5 1433.84   560.6 1437.65
   570.7 1440.86   611.1 1452.37   621.2 1456.18   641.3 1465.26   671.6 1481.23
   681.7 1486.95   701.9 1499.46   782.6  1557.2   812.9 1576.94   833.1 1589.06
#Mann= 3 , 0 , 0
      10     .08       0   329.4    .045       0   459.7     .08       0
Bank Sta=329.4,459.7
XS Rating Curve= 0 ,0
Exp/Cntr=0.3,0.1

Type RM Length L Ch R = 1 ,9930.4  ,73.9,70.8,67.7
XS GIS Cut Line= 4
      1774252.05      183782.543     1774337.713      183601.609
     1774444.793      183249.027     1774547.983      183033.344
#Sta/Elev= 30
      10 1552.85    60.1 1517.86   150.1 1456.71   170.2 1444.27   200.2 1427.82
   230.1 1414.13     250 1406.53   259.9 1403.75   269.9 1402.46   309.7  1402.4
   369.5 1402.36   439.2  1402.4     499  1402.4   508.9 1402.93   518.9 1406.68
   528.8 1412.72   548.8 1426.04   558.7 1431.18   568.7 1435.06   618.5 1449.08
   628.4 1452.53   638.4 1456.97   648.4 1462.56   658.3 1468.97   698.2 1496.49
   708.1 1504.25     738 1529.16     758  1544.1   767.9 1552.13   807.8 1589.43
#Mann= 3 , 0 , 0
      10     .08       0   309.7    .045       0   439.2     .08       0
Bank Sta=309.7,439.2
XS Rating Curve= 0 ,0
Exp/Cntr=0.3,0.1

Type RM Length L Ch R = 1 ,9859.6  ,81.9,79.7,77.4
XS GIS Cut Line= 4
     1774322.047       183794.14     1774423.603      183618.955
     1774491.804       183254.25     1774575.937      183073.091
#Sta/Elev= 30
     9.6 1540.24    38.6 1519.81    77.1 1491.55    96.4 1479.15     135 1455.22
   154.3 1443.83   173.6 1433.32   192.9  1424.4   232.6 1410.55   242.6 1408.07
   262.7 1404.14   272.7 1402.88   282.7 1402.45   342.9  1402.4     403 1402.35
   453.2  1402.4   523.4  1402.5   533.4 1404.84   543.4 1410.49   563.5 1423.75
   573.5 1428.44   603.5 1435.57   613.5 1438.81   623.5 1443.11   633.4 1448.14
   643.4 1454.28   653.4 1461.77   693.4 1493.44   723.3 1518.01   773.3 1555.99
#Mann= 3 , 0 , 0
     9.6     .08       0   342.9    .045       0   453.2     .08       0
Bank Sta=342.9,453.2
XS Rating Curve= 0 ,0
Exp/Cntr=0.3,0.1

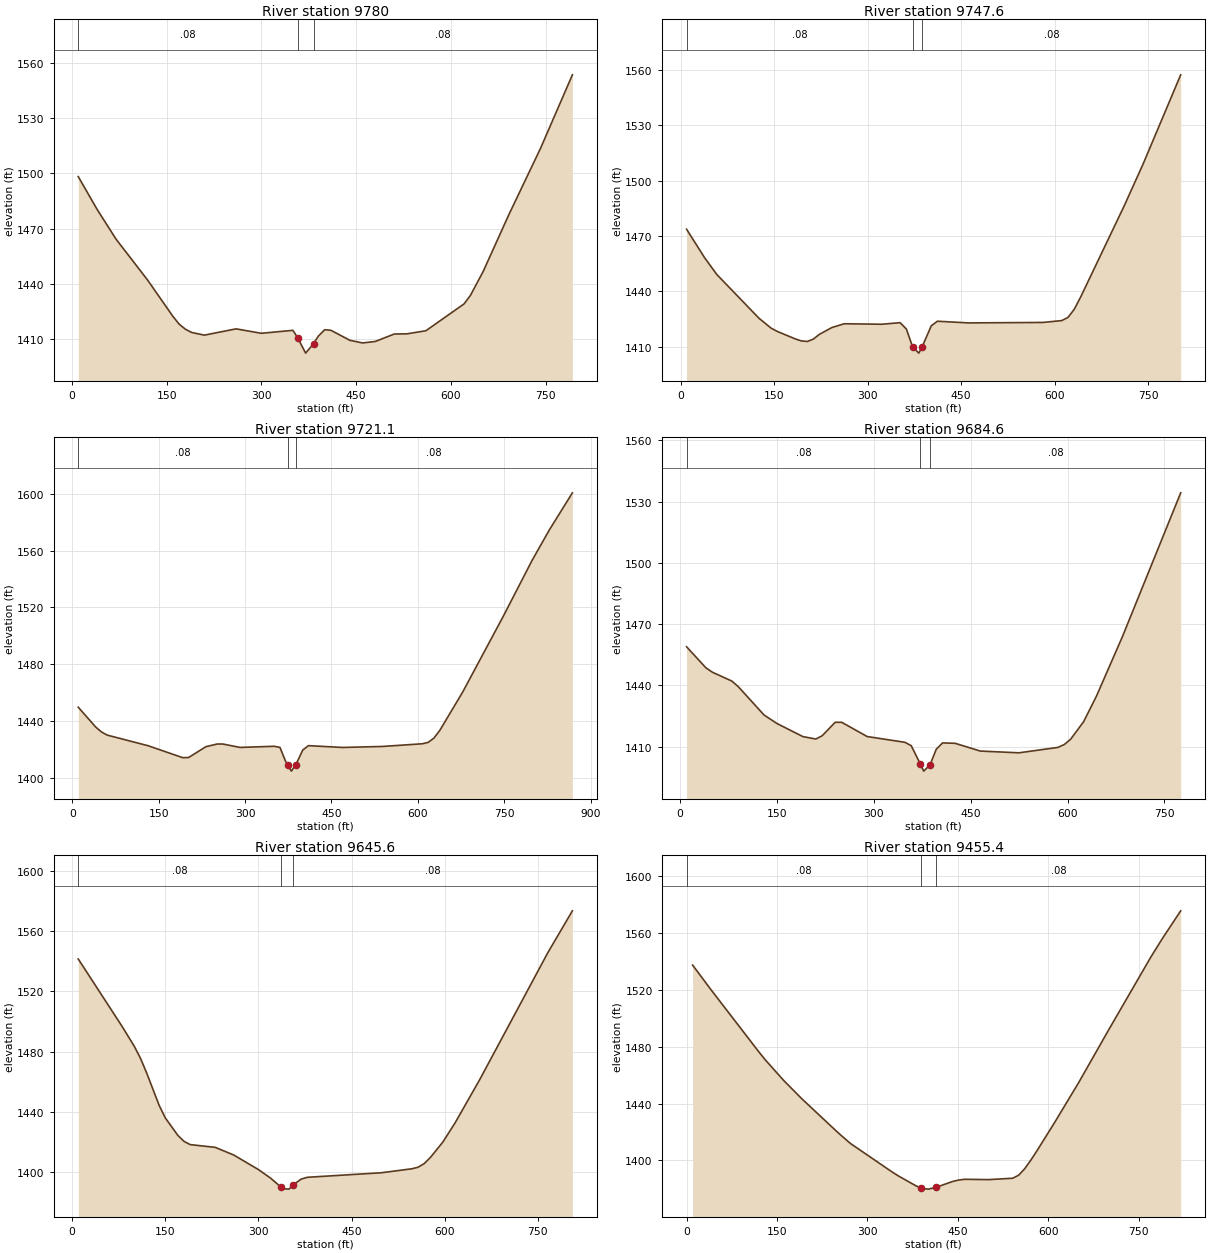
Type RM Length L Ch R = 1 ,9780    ,31.9,32.4,32.9
XS GIS Cut Line= 4
     1774405.774      183838.857     1774510.243      183657.082
     1774545.762      183308.156     1774611.665      183085.788
#Sta/Elev= 30
      10 1498.22    39.9 1480.39    69.9 1464.22   119.8 1442.03   159.7 1422.39
   169.7  1418.1   179.7 1415.31   189.7 1413.55   209.7 1412.11   259.8 1415.52
   299.8 1413.12   349.9 1414.72   357.5 1410.58     370 1402.34   382.5 1407.47
     390 1411.53   400.1 1415.05   410.1 1414.73   440.1 1409.29   460.2 1407.87
   480.2 1408.67   510.3 1412.71   530.3 1412.81   560.4  1414.5   620.9 1429.11
     631 1433.76   651.1 1446.72   691.5  1477.4   741.9 1513.61   792.3  1553.5
#Mann= 3 , 0 , 0
      10     .08       0   357.5    .045       0   382.5     .08       0
Bank Sta=357.5,382.5
XS Rating Curve= 0 ,0
Exp/Cntr=0.3,0.1

Type RM Length L Ch R = 1 ,9747.6  ,26.1,26.5,26.9
XS GIS Cut Line= 4
     1774448.992       183862.69     1774539.494      183659.171
     1774583.371       183293.53     1774649.566      183093.402
#Sta/Elev= 30
     9.7 1473.71    38.7 1458.24    58.1 1449.22   125.9 1425.45   145.3 1420.11
   154.9 1418.37     184 1414.29   193.7  1413.2   203.4  1412.9   213.1 1414.22
   222.7 1416.77   242.6 1420.45   262.5  1422.5   322.3 1422.23   352.1 1423.08
   362.1 1419.62     372 1410.03     382 1406.59  387.23 1409.89   401.9 1421.35
   411.8 1423.87   461.6 1422.96     581 1423.21   611.1 1424.21   621.1 1425.93
   631.1 1430.31   641.2 1436.82   711.5 1486.55   741.6 1509.09   801.8 1557.33
#Mann= 3 , 0 , 0
     9.7     .08       0     372    .045       0  387.23     .08       0
Bank Sta=372,387.23
XS Rating Curve= 0 ,0
Exp/Cntr=0.3,0.1

Type RM Length L Ch R = 1 ,9721.1  ,35.3,36.5,37.7
XS GIS Cut Line= 4
     1774490.655       183877.51     1774560.704       183677.35
     1774614.711      183285.173     1774705.315      183040.836
#Sta/Elev= 30
    10.1 1449.68    40.4  1435.7    50.5  1432.2    60.6 1429.98   131.3 1422.54
   191.9 1414.07     202 1414.24   231.9 1421.86   251.7 1423.73   261.5 1423.71
   291.2 1421.32   350.6 1422.13   360.5 1421.35   370.4 1411.41   373.9 1409.09
   380.3 1404.62  388.02 1409.09   400.1 1419.49     410 1422.57   469.4  1421.3
   538.7 1422.01   607.9  1423.9     618  1424.9     628 1427.92     638 1433.21
   678.1 1460.48   748.3 1513.65   798.4 1553.07   828.4 1574.57   868.5 1600.75
#Mann= 3 , 0 , 0
    10.1     .08       0   373.9    .045       0  388.02     .08       0
Bank Sta=373.9,388.02
XS Rating Curve= 0 ,0
Exp/Cntr=0.3,0.1

Type RM Length L Ch R = 1 ,9684.6  ,42.5,39.1,35.6
XS GIS Cut Line= 4
     1774572.767      183896.733     1774598.884      183627.726
     1774635.448      183426.624     1774692.906      183131.499
#Sta/Elev= 30
      10 1458.89      40 1448.58    50.1 1446.41    80.1  1442.1    90.1 1439.35
   130.1 1425.45   150.2 1421.28   190.2  1414.9   210.2  1413.7   220.2 1415.35
   240.2 1421.91   250.3  1421.9   289.7 1414.93   348.1 1412.11   357.9 1410.47
  371.86 1401.63   377.3 1397.99   387.1  1401.1   396.8 1408.75   406.5 1411.81
     426 1411.61   464.9 1407.82   524.8 1406.96   584.9 1409.59   594.9 1410.99
     605 1413.67     625 1422.23     645 1434.84   685.1 1463.89   775.3 1534.28
#Mann= 3 , 0 , 0
      10     .08       0  371.86    .045       0   387.1     .08       0
Bank Sta=371.86,387.1
XS Rating Curve= 0 ,0
Exp/Cntr=0.3,0.1

Type RM Length L Ch R = 1 ,9645.6  ,202.8,190.1,174.3
XS GIS Cut Line= 4
     1774725.733      183865.229     1774649.566      183626.572
     1774664.799      183370.143     1774725.733      183078.168
#Sta/Elev= 30
      10 1541.41    80.2 1496.92   100.2 1483.49   110.2 1475.51   120.2 1465.73
   140.3 1444.23   150.3 1435.86   170.4 1424.33   180.4 1420.32   190.4 1418.19
   230.5 1416.39   260.4 1411.29   299.9  1401.7   319.7 1395.95   336.8 1389.89
   339.4  1388.9   349.3 1388.65  355.31 1391.13   369.1 1395.35     379 1396.51
   497.5 1399.49   547.2 1402.15   557.1 1403.17   567.1 1405.61     577 1409.65
   596.9 1419.78   616.8 1432.63   656.5 1461.37   765.9 1545.42   805.7 1573.38
#Mann= 3 , 0 , 0
      10     .08       0   336.8    .045       0  355.31     .08       0
Bank Sta=336.8,355.31
XS Rating Curve= 0 ,0
Exp/Cntr=0.3,0.1

Type RM Length L Ch R = 1 ,9455.4  ,228.5,230.1,231.8
XS GIS Cut Line= 4
     1774806.457      183861.209     1774834.906      183591.027
     1774720.299      183250.612     1774765.251      183067.058
#Sta/Elev= 30
    10.1 1537.52    40.2 1520.37   120.7 1475.97   130.8 1470.68     161 1456.31
   191.2 1443.35   251.6 1419.34   271.7  1411.9   341.5 1391.63   351.5 1388.96
   381.4  1381.8   388.9  1380.5   391.4 1380.07   401.4 1379.67   413.9 1380.92
   441.3 1385.04   451.3 1386.05   461.2  1386.6   501.2 1386.37   541.1 1387.34
     551  1389.5     561 1394.06     571 1399.98     581 1406.47   610.9 1426.81
   650.8 1454.94   700.5 1492.05   770.1 1543.09     790 1556.66   819.8 1575.77
#Mann= 3 , 0 , 0
       0     .08       0   388.9    .045       0   413.9     .08       0
Bank Sta=388.9,413.9
XS Rating Curve= 0 ,0
Exp/Cntr=0.3,0.1

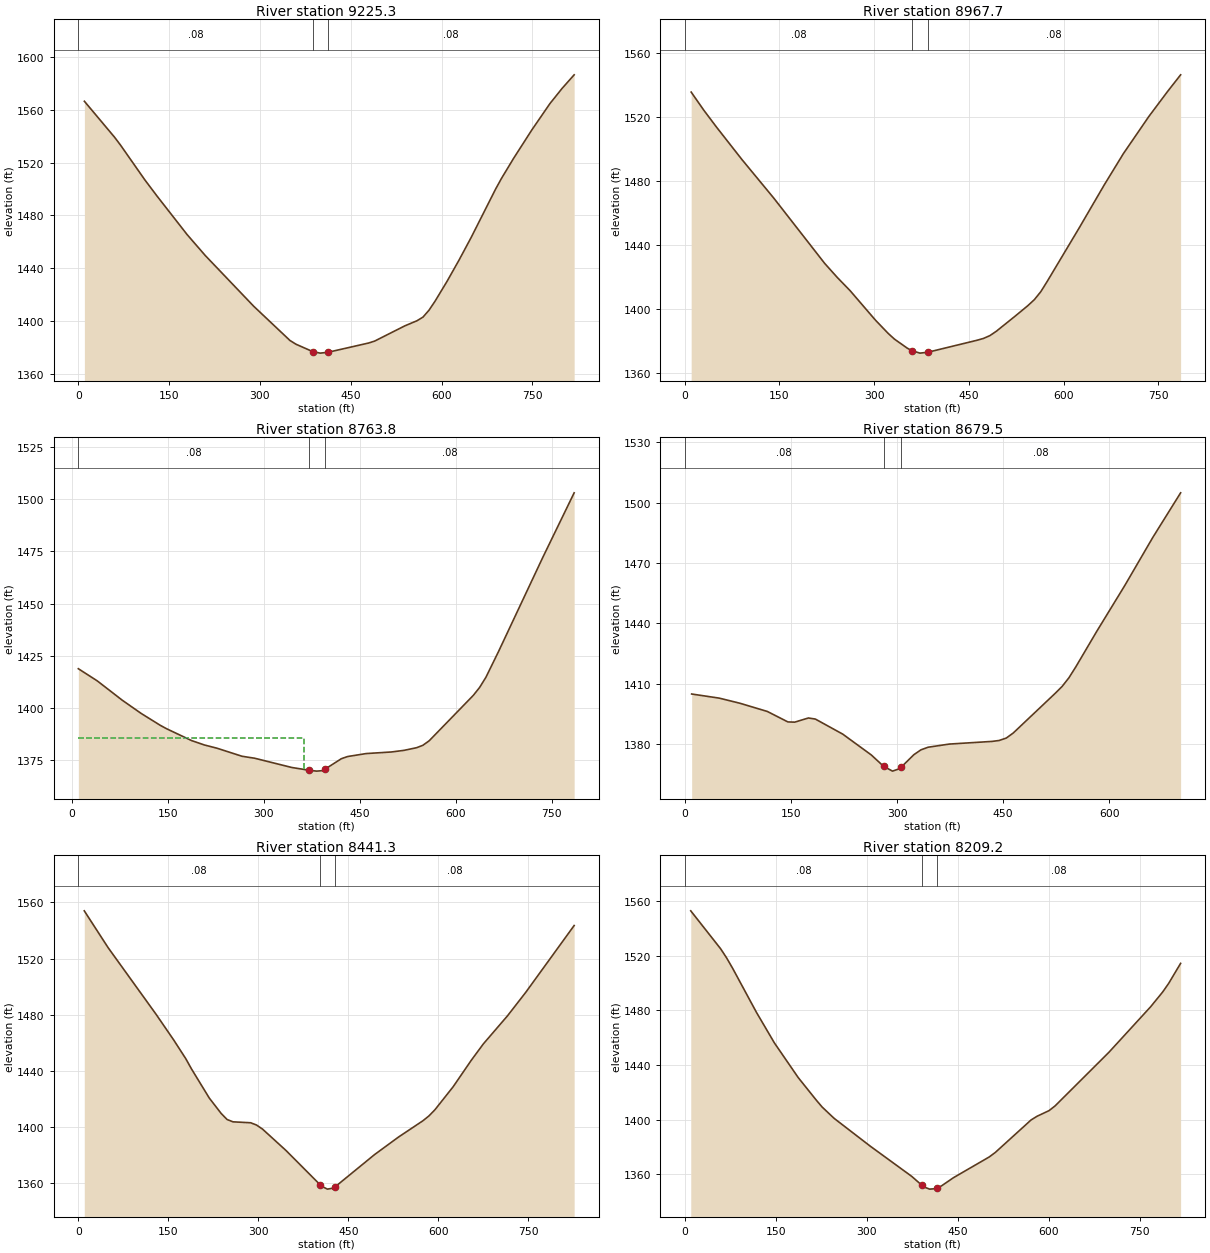
Type RM Length L Ch R = 1 ,9225.3  ,263.6,257.6,251.6
XS GIS Cut Line= 3
     1775119.653      183793.508     1775012.618      183398.244
     1774905.582       183002.98
#Sta/Elev= 30
      10 1566.68    59.9 1539.37    69.9 1533.28   109.9 1507.01   129.8 1494.86
   179.8 1465.46   209.7 1449.62   289.6 1411.18   349.6 1385.15   359.6  1382.3
     387 1376.75   399.5 1375.56     412 1376.16   479.4 1383.22   489.4 1384.68
   539.3 1396.25   559.3 1400.11   569.3 1402.89   579.3 1408.16   589.3 1415.02
   609.3 1430.23   629.2 1446.45   649.2 1463.62   689.2 1499.99   699.1 1508.25
   719.1 1523.45   749.1 1544.93     779 1564.92     799 1576.39     819 1586.74
#Mann= 3 , 0 , 0
       0     .08       0     387    .045       0     412     .08       0
Bank Sta=387,412
XS Rating Curve= 0 ,0
Exp/Cntr=0.3,0.1

Type RM Length L Ch R = 1 ,8967.7  ,216.9,203.9,190.7
XS GIS Cut Line= 3
     1775360.864      183673.909     1775304.674      183407.943
     1775065.884      182953.294
#Sta/Elev= 30
    10.1 1535.58    30.2 1524.21    50.3 1513.65    90.6 1493.37     141 1469.27
   221.5 1428.53   241.6 1419.67   261.8 1411.47     302 1393.01   322.2  1384.7
   332.3 1381.09   352.4  1375.5     360 1373.87   372.5 1372.39     385 1372.94
   463.2 1380.46   473.2 1381.59   483.3 1383.34   493.4 1386.04   523.6 1395.61
   543.7 1402.17   553.8 1405.86   563.9  1410.8   573.9 1417.11   624.3 1450.39
   664.5  1477.6   694.8 1497.14     735 1520.29   765.2  1536.2   785.4 1546.37
#Mann= 3 , 0 , 0
       0     .08       0     360    .045       0     385     .08       0
Bank Sta=360,385
XS Rating Curve= 0 ,0
Exp/Cntr=0.3,0.1

Type RM Length L Ch R = 1 ,8763.8  ,94.6,84.2,74.2
XS GIS Cut Line= 4
     1775631.116      183563.242     1775523.383      183298.806
     1775386.268      183191.073     1775121.831      183001.723
#Sta/Elev= 30
     9.8 1418.85    39.4 1413.02    78.8 1403.69   108.3 1397.38   137.8 1391.76
   147.7 1390.11   187.1  1384.4   206.8 1382.33   226.5 1380.78   265.8 1376.91
   285.5 1375.97   343.7 1371.53   369.9 1370.25   382.4 1369.79   392.1 1370.03
   394.9 1370.59   421.2 1375.75   430.9 1376.78   459.9  1378.2   499.3 1378.96
   519.1 1379.74   538.8 1381.01   548.6 1382.16   558.5 1384.33   627.5 1406.08
   637.3 1409.85   647.2 1414.74   666.9 1427.05   735.9 1472.01   785.2  1503.1
#Mann= 3 , 0 , 0
     9.8     .08       0   369.9    .045       0   394.9     .08       0
#XS Ineff= 2 , 0
          362.36 1385.64
Permanent Ineff=
       F       F
Bank Sta=369.9,394.9
XS Rating Curve= 0 ,0
Exp/Cntr=0.3,0.1

Type RM Length L Ch R = 1 ,8679.5  ,239.2,238.2,237.3
XS GIS Cut Line= 4
     1775731.717      183314.294     1775548.164       183186.93
      1775327.15      183119.502     1775147.342      182950.932
#Sta/Elev= 30
     9.7 1404.84    48.6  1402.8    77.7 1400.27   116.6 1396.18   145.7 1390.97
   155.4 1390.85   174.8 1392.92   184.6 1392.38   223.4 1384.87   263.6 1374.55
   281.2 1368.85   293.7 1366.49   303.8 1367.73   306.2 1368.56   323.9 1374.67
   333.9 1377.08     344 1378.38   374.1 1379.95   434.4 1381.27   444.4 1381.73
   454.5 1382.93   464.3 1385.43   523.5 1405.12   533.4 1408.58   543.2 1412.98
   553.1 1418.51   582.6 1436.11   622.1 1458.82   661.5 1482.62     701  1504.9
#Mann= 3 , 0 , 0
       0     .08       0   281.2    .045       0   306.2     .08       0
Bank Sta=281.2,306.2
XS Rating Curve= 0 ,0
Exp/Cntr=0.3,0.1

Type RM Length L Ch R = 1 ,8441.3  ,229.7,232.1,234.6
XS GIS Cut Line= 4
     1775915.271       183055.82     1775738.165      182990.073
     1775424.546       182905.98     1775115.195      182858.844
#Sta/Elev= 30
     9.9    1554    49.7 1527.71   129.3  1480.4   159.1 1461.83     179 1448.63
   188.9 1441.07   218.4 1420.43   238.1 1409.51     248 1405.19   257.8 1403.54
   287.3 1402.87   297.1 1401.23     307 1398.37   346.3 1383.05   402.7  1358.8
   405.4 1357.62   415.2 1355.55   425.1 1356.29   427.7 1357.08   493.9 1380.21
   533.8 1392.71   574.2 1404.24   584.3  1407.7   594.4 1412.13   624.7  1428.5
   654.9 1447.35   675.1 1459.09   715.5 1479.18   745.8 1495.87   826.5 1543.53
#Mann= 3 , 0 , 0
       0     .08       0   402.7    .045       0   427.7     .08       0
Bank Sta=402.7,427.7
XS Rating Curve= 0 ,0
Exp/Cntr=0.3,0.1

Type RM Length L Ch R = 1 ,8209.2  ,153.2,150.4,146
XS GIS Cut Line= 4
     1775960.223       182849.79     1775720.479      182759.887
     1775443.276      182658.745      1775177.31      182647.507
#Sta/Elev= 30
     9.8 1552.87    59.1 1525.07    68.9 1518.42    78.8 1510.83   118.2 1478.45
   147.7 1456.14   187.1 1430.68   216.7 1414.26   226.5 1409.13   246.2 1400.88
   305.2  1380.7   374.1  1358.4   391.1 1351.78   393.7 1350.75   403.6 1349.07
   413.4 1349.39   416.1 1349.96   423.3 1351.49   442.9 1357.45   501.9 1372.65
   511.8 1375.92   570.8 1399.72   580.7 1402.44   600.4 1406.55   610.3 1409.98
     699 1449.22     768 1482.68   787.7 1493.42   797.6 1499.73   817.3 1514.41
#Mann= 3 , 0 , 0
       0     .08       0   391.1    .045       0   416.1     .08       0
Bank Sta=391.1,416.1
XS Rating Curve= 0 ,0
Exp/Cntr=0.3,0.1