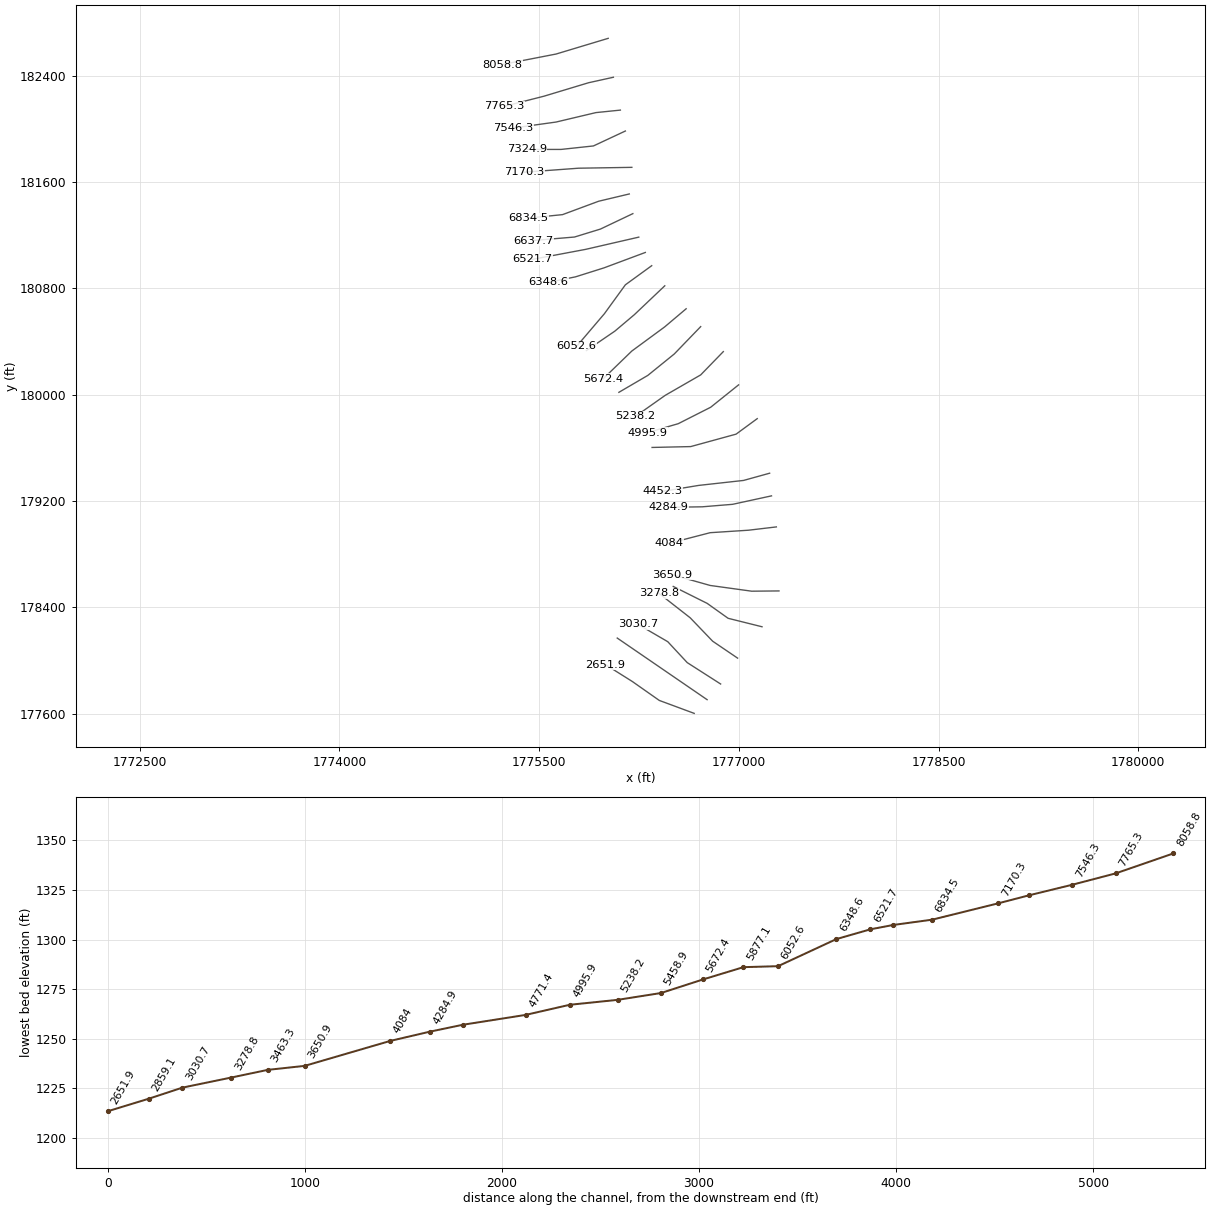
HEC-RAS study Twin Branch.prj: Twin Branch

--- Twin Branch.g01 (geometry) --- (continued)

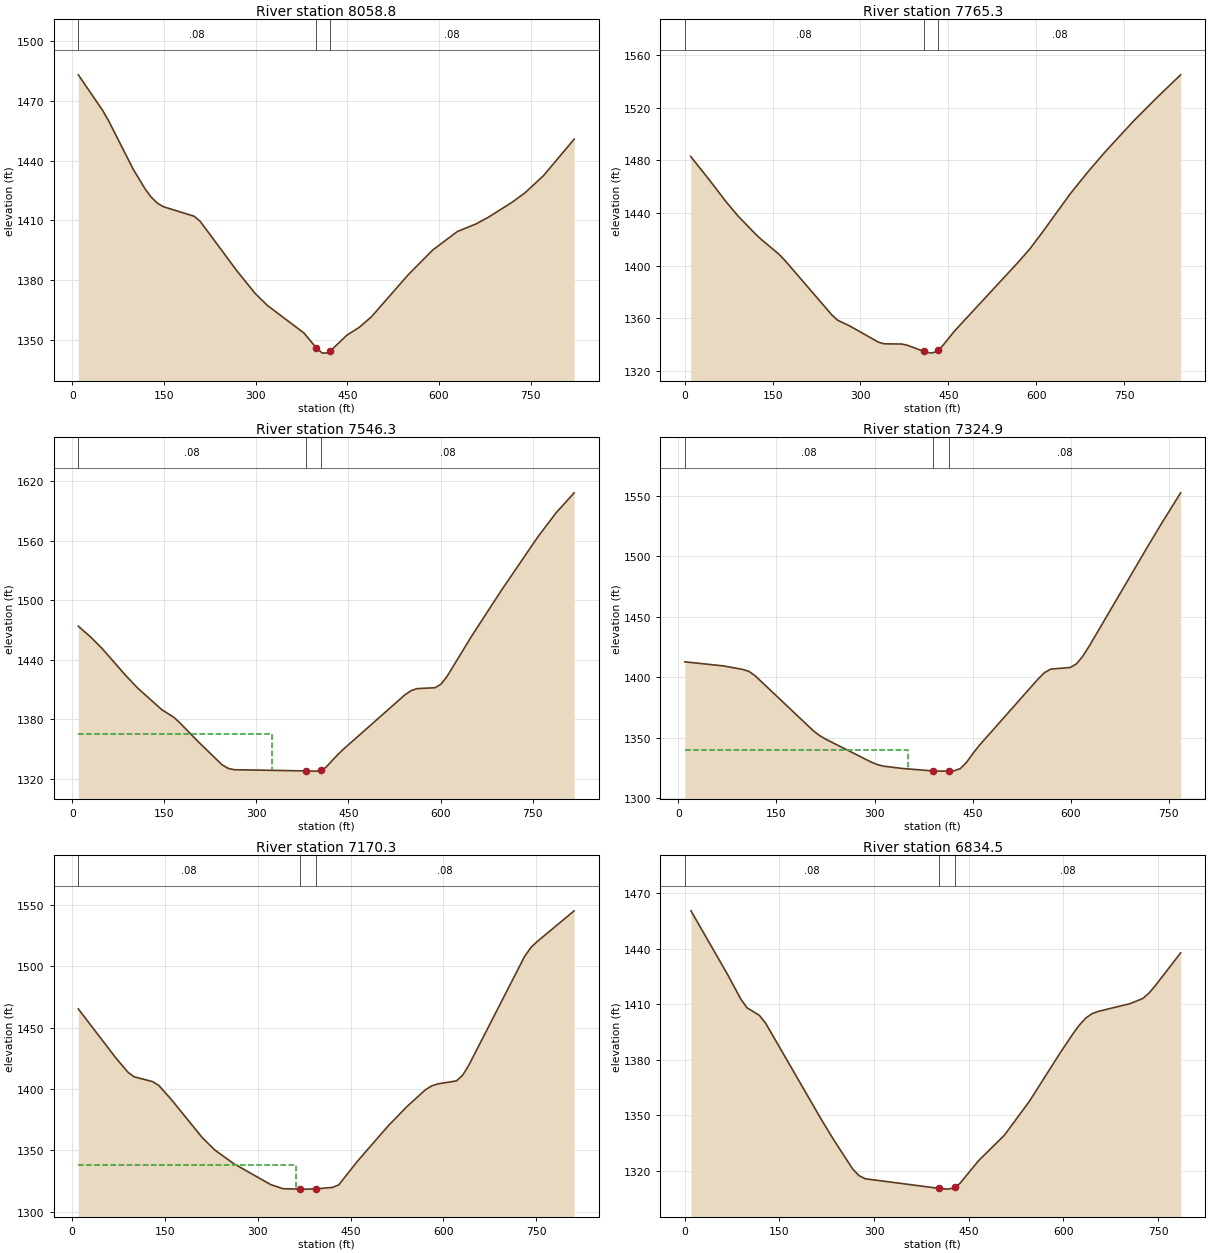
Type RM Length L Ch R = 1 ,8058.8  ,293.1,293.5,295.4
XS GIS Cut Line= 3
     1776018.614      182681.923     1775627.004      182563.746
     1775222.567      182484.986
#Sta/Elev= 30
      10 1482.99    49.9 1465.09    59.9 1459.74    99.8 1435.64   119.7 1425.58
   129.7  1421.5   139.7 1418.56   149.7 1416.82   199.5  1412.1   209.5  1409.5
   269.4 1384.73   299.3 1373.38   319.3 1367.39   379.1 1353.56   399.1 1346.18
   409.1 1343.48   419.1 1343.68   421.6 1344.36   449.3 1352.47   469.4 1356.36
   489.4 1361.68   549.7 1382.79   589.9 1395.21   630.1 1404.45   660.3 1408.21
   680.4 1411.53   720.6 1419.32   740.7 1423.84   770.8  1432.4   821.1 1450.74
#Mann= 3 , 0 , 0
      10     .08       0   399.1    .045       0   421.6     .08       0
Bank Sta=399.1,421.6
XS Rating Curve= 0 ,0
Exp/Cntr=0.3,0.1

Type RM Length L Ch R = 1 ,7765.3  ,220.6,219,217.3
XS GIS Cut Line= 4
     1776057.619      182389.033     1775871.169      182347.734
     1775536.925      182246.686     1775240.024      182170.663
#Sta/Elev= 30
    10.1 1482.99    40.2 1466.17    70.4  1448.6    90.5 1437.91   120.6 1424.07
   130.7 1419.85   160.8 1408.65   170.9 1403.97   250.8 1362.61   260.8 1358.46
   280.8 1354.27   330.6 1341.74   340.6 1340.47   370.5  1340.3   380.5 1339.32
   407.9 1334.75   420.4 1333.39   430.4 1334.56   432.9  1335.7   440.4 1339.09
   460.3 1350.08   569.8 1402.84   589.6 1412.93   609.4 1424.64   658.8 1455.02
   688.4 1471.32   718.1 1486.71   767.5 1510.57   807.1 1528.24   846.6 1545.12
#Mann= 3 , 0 , 0
       0     .08       0   407.9    .045       0   432.9     .08       0
Bank Sta=407.9,432.9
XS Rating Curve= 0 ,0
Exp/Cntr=0.3,0.1

Type RM Length L Ch R = 1 ,7546.3  ,224.9,221.4,218
XS GIS Cut Line= 4
     1776110.062      182141.798     1775926.509      182123.068
     1775626.829      182051.894     1775304.674      182006.942
#Sta/Elev= 30
     9.7 1473.78    29.1 1463.27    48.6  1451.2    87.4 1423.78   106.8 1411.21
   145.7 1389.65   165.1 1382.08   174.8 1376.63   204.4  1357.8   244.1    1334
   254.1 1330.43     264 1329.12   380.7 1327.91   393.2 1327.69   403.1 1327.88
   405.7 1328.81     413 1331.42   432.9 1344.58   442.8 1350.38   541.8  1404.5
   551.7 1408.73   561.5 1410.85   591.1 1411.75   600.9 1415.43   610.8 1423.35
   650.2 1463.25   699.5  1510.2   758.7 1563.87   788.2 1587.94   817.8 1608.22
#Mann= 3 , 0 , 0
     9.7     .08       0   380.7    .045       0   405.7     .08       0
#XS Ineff= 2 , 0
          325.75  1365.4
Permanent Ineff=
       F       F
Bank Sta=380.7,405.7
XS Rating Curve= 0 ,0
Exp/Cntr=0.3,0.1

Type RM Length L Ch R = 1 ,7324.9  ,155.9,154.5,153.6
XS GIS Cut Line= 4
     1776147.522      181984.466     1775907.779      181872.086
     1775664.289      181845.864     1775405.816      181845.864
#Sta/Elev= 30
     9.8 1412.72    68.6 1409.34    98.1 1406.46   107.9 1404.82   117.7 1401.02
   205.9 1355.94   215.7 1351.81   225.5 1348.69   294.2 1329.98     304 1327.76
   313.8 1326.41   343.1 1324.48   389.4 1322.48   401.9 1322.31   414.4 1322.41
   421.5 1322.59   431.3 1324.45   441.1 1329.84   450.9 1337.26   460.7 1343.88
   549.4 1398.08   559.4 1403.57   569.3 1406.67   599.1 1408.01   609.1 1411.14
     619 1417.72     629 1426.33   718.4 1508.68   738.3 1526.56   768.1 1552.47
#Mann= 3 , 0 , 0
     9.8     .08       0   389.4    .045       0   414.4     .08       0
#XS Ineff= 2 , 0
          351.63 1340.11
Permanent Ineff=
       F       F
Bank Sta=389.4,414.4
XS Rating Curve= 0 ,0
Exp/Cntr=0.3,0.1

Type RM Length L Ch R = 1 ,7170.3  ,325.1,335.8,345.3
XS GIS Cut Line= 3
      1776196.22      181711.008     1775795.322      181704.505
     1775385.949      181674.381
#Sta/Elev= 30
      10 1465.35    70.2 1425.63    90.2 1413.68   100.2 1409.97   130.3 1405.99
   140.3 1402.79   160.4 1391.38   210.5 1360.23   230.5 1350.28   260.6 1339.31
   320.8 1322.04   340.8 1318.64   368.4 1318.33   380.9 1318.31   393.4 1318.54
     421 1319.69     431 1321.83     461 1340.98   511.1 1370.06   541.1 1385.64
   571.1 1399.41   581.2 1402.58   591.2 1404.18   621.2 1406.65   631.2 1411.28
   641.2 1419.47   731.3 1508.18   741.3 1515.34   751.4  1520.2   811.4 1545.38
#Mann= 3 , 0 , 0
      10     .08       0   368.4    .045       0   393.4     .08       0
#XS Ineff= 2 , 0
          361.21 1338.29
Permanent Ineff=
       F       F
Bank Sta=368.4,393.4
XS Rating Curve= 0 ,0
Exp/Cntr=0.3,0.1

Type RM Length L Ch R = 1 ,6834.5  ,198.3,196.8,195.4
XS GIS Cut Line= 4
     1776176.922      181510.725     1775947.249      181456.088
     1775675.527      181355.139     1775417.054      181328.917
#Sta/Elev= 30
     9.8 1460.57    68.9 1425.48    88.5    1413    98.4  1408.2     118 1404.08
   127.9 1399.93   216.4 1347.72   236.1 1336.66   266.1 1320.93   276.1 1317.35
   286.1 1315.65   403.5 1310.44     416 1310.05     426 1310.58   428.5 1311.22
     436 1313.14     466 1325.61     506 1339.01   545.9 1357.44   595.9 1384.26
   615.9 1394.43   625.9 1399.01   635.9  1402.7   645.9 1405.03   655.9 1406.23
   705.8 1410.38   725.8 1413.16   735.8 1416.12   745.8 1420.16   785.8 1437.82
#Mann= 3 , 0 , 0
       0     .08       0   403.5    .045       0   428.5     .08       0
Bank Sta=403.5,428.5
XS Rating Curve= 0 ,0
Exp/Cntr=0.3,0.1

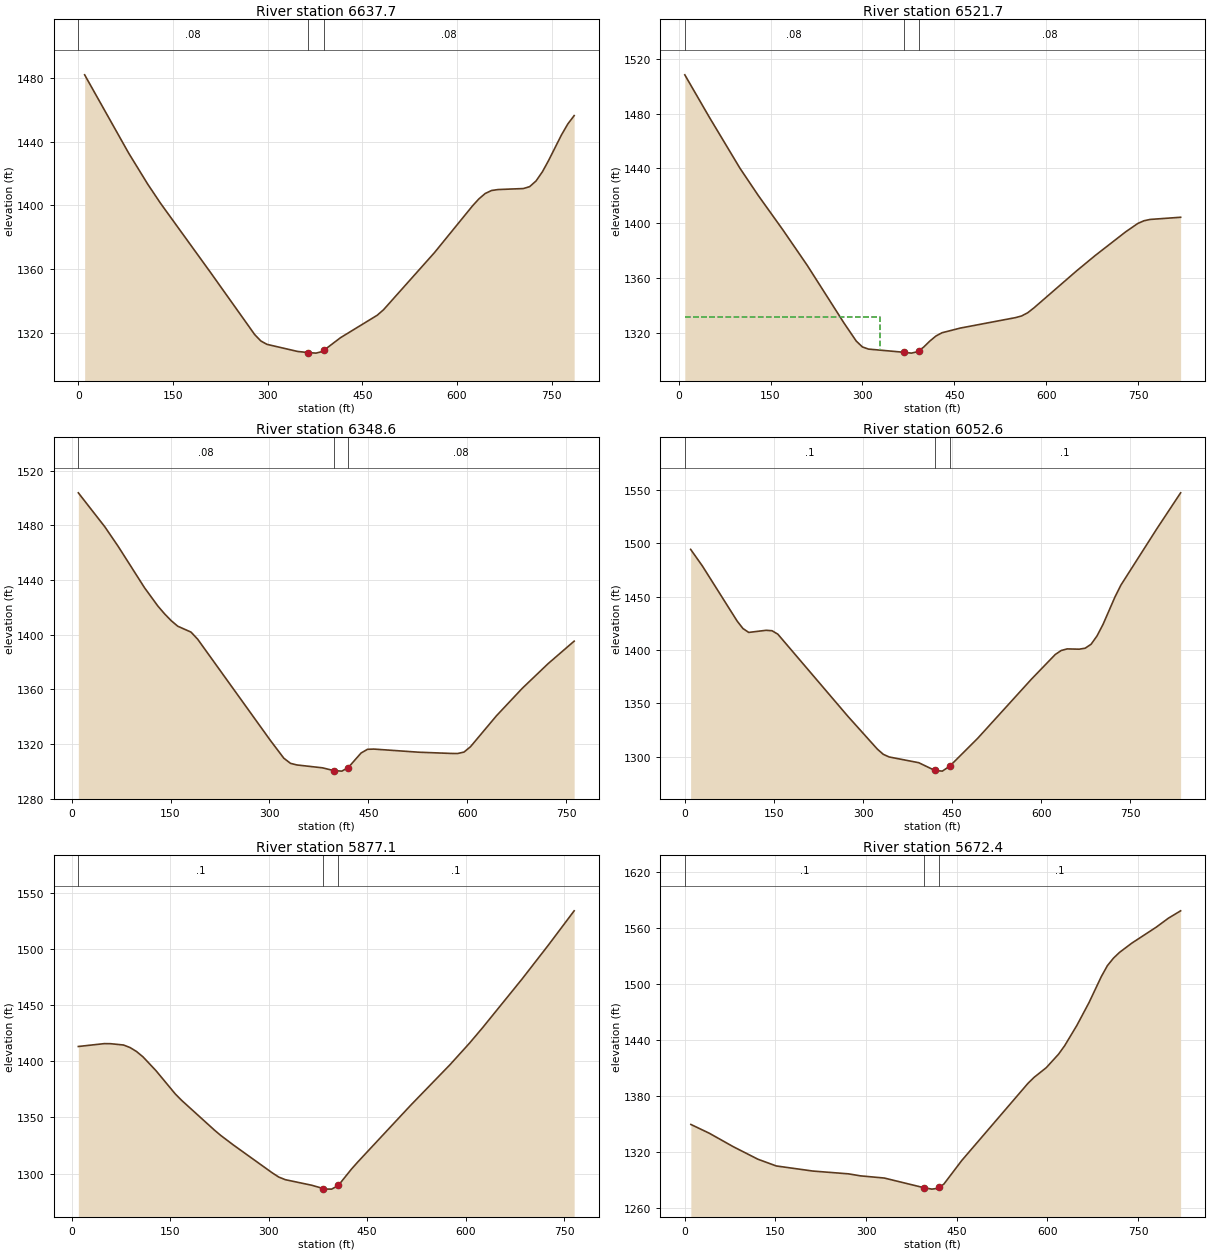
Type RM Length L Ch R = 1 ,6637.7  ,118,116.1,113.9
XS GIS Cut Line= 4
     1776203.712      181362.631     1775960.223      181246.505
     1775765.431      181186.569     1775454.514      181160.347
#Sta/Elev= 30
      10 1481.89    79.9  1432.7   109.9 1413.38   129.9 1401.54   209.8 1357.78
   279.5 1318.99   289.2 1315.01   298.9 1312.89   347.4 1308.44     364 1307.75
   376.5 1307.39   386.2 1308.36     389 1309.13   415.3 1317.04   473.6 1331.15
   483.6  1334.6   564.2 1370.38   624.5 1399.69   634.6 1404.08   644.7 1407.49
   654.7 1409.35   664.8 1409.95   705.1 1410.58   715.1 1411.78   725.2 1415.34
   735.3 1421.09   745.3 1428.33   765.5 1444.21   775.5 1451.04   785.6 1456.31
#Mann= 3 , 0 , 0
       0     .08       0     364    .045       0     389     .08       0
Bank Sta=364,389
XS Rating Curve= 0 ,0
Exp/Cntr=0.3,0.1

Type RM Length L Ch R = 1 ,6521.7  ,170.9,173.1,175.5
XS GIS Cut Line= 3
     1776248.151      181185.763     1775848.723       181093.67
     1775446.367      181017.901
#Sta/Elev= 30
      10 1508.29      50 1477.38     100 1440.15     130  1420.2     170  1395.2
     210 1369.15   269.9 1327.14   289.9 1313.97   299.9 1309.72   309.9 1308.14
   367.4 1305.83   379.9  1305.2   389.9 1306.24   392.4 1307.08   399.9 1309.61
   409.9 1313.97   419.9 1317.68   429.9 1320.08   459.8 1323.49   549.7  1331.1
   559.7 1332.32   569.7 1334.66   579.7 1338.15   649.6 1365.26   679.5  1376.3
   729.5 1393.67   749.4 1399.82   759.4 1401.78   769.4 1402.75   819.3 1404.35
#Mann= 3 , 0 , 0
      10     .08       0   367.4    .045       0   392.4     .08       0
#XS Ineff= 2 , 0
          328.98 1331.57
Permanent Ineff=
       F       F
Bank Sta=367.4,392.4
XS Rating Curve= 0 ,0
Exp/Cntr=0.3,0.1

Type RM Length L Ch R = 1 ,6348.6  ,277.8,295.9,314.1
XS GIS Cut Line= 4
     1776297.362      181070.444     1775986.445      180954.318
     1775772.923       180886.89     1775570.639      180845.684
#Sta/Elev= 30
    10.1 1503.89    50.3 1479.02    70.4 1464.82   110.6 1434.38   130.7 1421.09
   140.8 1415.41   150.9 1410.38   160.9 1406.29     181 1401.99   191.1 1396.81
   301.7 1322.54   321.8 1309.72   331.9 1305.96   341.6 1304.78   380.6 1302.66
   397.3 1300.67   409.8 1300.26   419.5 1302.85     439 1313.52   448.7 1316.21
   458.5 1316.39   526.6  1314.1   575.5 1313.21   585.3 1313.13   595.1  1314.2
     605 1318.14   644.3 1340.74   683.6  1360.9   722.9 1378.99   762.2 1395.36
#Mann= 3 , 0 , 0
    10.1     .08       0   397.3    .045       0   419.5     .08       0
Bank Sta=397.3,419.5
XS Rating Curve= 0 ,0
Exp/Cntr=0.3,0.1

Type RM Length L Ch R = 1 ,6052.6  ,182.5,175.6,168.7
XS GIS Cut Line= 4
     1776345.324      180970.892     1776147.522      180826.954
     1775990.191      180609.686     1775782.031      180364.613
#Sta/Elev= 30
     9.8  1494.5    29.4 1479.09    88.1 1427.28    97.9 1420.26   107.6 1416.63
     137 1418.62   146.8 1418.21   156.6 1414.97   274.4 1338.03   324.1 1307.19
     334 1302.36     344 1299.85   393.7 1294.49   420.9 1287.22   433.4 1286.59
   445.9 1291.26     493 1317.41   583.2 1372.73   623.4 1395.92   633.5 1399.68
   643.5 1401.18   663.6 1400.91   673.7 1401.81   683.7 1405.53   693.7 1413.34
   703.8 1424.12   723.9 1449.84   733.9 1460.99   794.2 1513.65   834.4  1547.5
#Mann= 3 , 0 , 0
       0      .1       0   420.9    .045       0   445.9      .1       0
Bank Sta=420.9,445.9
XS Rating Curve= 0 ,0
Exp/Cntr=0.3,0.1

Type RM Length L Ch R = 1 ,5877.1  ,206.5,204.7,202.8
XS GIS Cut Line= 4
     1776443.456      180819.462      1776214.95      180602.194
     1776068.857      180478.577     1775855.335      180332.483
#Sta/Elev= 30
     9.9 1413.34    49.3 1415.89    59.1 1415.83    78.8 1414.66    88.7  1412.4
    98.5  1408.9   108.4 1404.11   128.1 1391.86   157.7 1370.97   167.5 1365.19
   216.8 1339.01   226.6 1334.14   246.3 1325.42   305.5 1300.58   315.3 1296.87
   325.4 1294.51   365.7 1289.54   383.4 1286.56   385.8 1286.18   395.9  1286.1
     406 1289.34   426.1 1303.99   436.2 1310.62   516.6 1361.09   576.3 1397.15
   606.2 1416.49   626.1 1430.27   685.8 1473.39   725.6 1503.39   765.4 1534.37
#Mann= 3 , 0 , 0
     9.9      .1       0   383.4    .045       0     406      .1       0
Bank Sta=383.4,406
XS Rating Curve= 0 ,0
Exp/Cntr=0.3,0.1

Type RM Length L Ch R = 1 ,5672.4  ,212.2,213.5,214.8
XS GIS Cut Line= 4
     1776604.018      180646.671     1776442.308      180509.902
      1776196.22      180328.737     1775978.687      180117.784
#Sta/Elev= 30
    10.1  1349.2    40.3 1339.88    80.7 1325.21     121 1311.95   151.3 1304.75
   211.8 1299.28   270.9 1296.28   290.7 1294.13   330.1 1291.79   396.4 1281.31
   408.9 1279.91   418.8 1280.76   421.4 1281.96   428.7 1285.34   458.2 1310.53
   567.9 1393.33     578  1399.7   598.2 1410.12   618.4 1424.49   628.5 1433.56
   648.7 1455.32   668.9 1479.88   689.1 1507.56   699.2 1519.33   709.3 1527.42
   719.4 1533.63   739.6 1543.48     780 1560.58   800.2 1570.23   820.4 1578.12
#Mann= 3 , 0 , 0
       0      .1       0   396.4    .045       0   421.4      .1       0
Bank Sta=396.4,421.4
XS Rating Curve= 0 ,0
Exp/Cntr=0.3,0.1

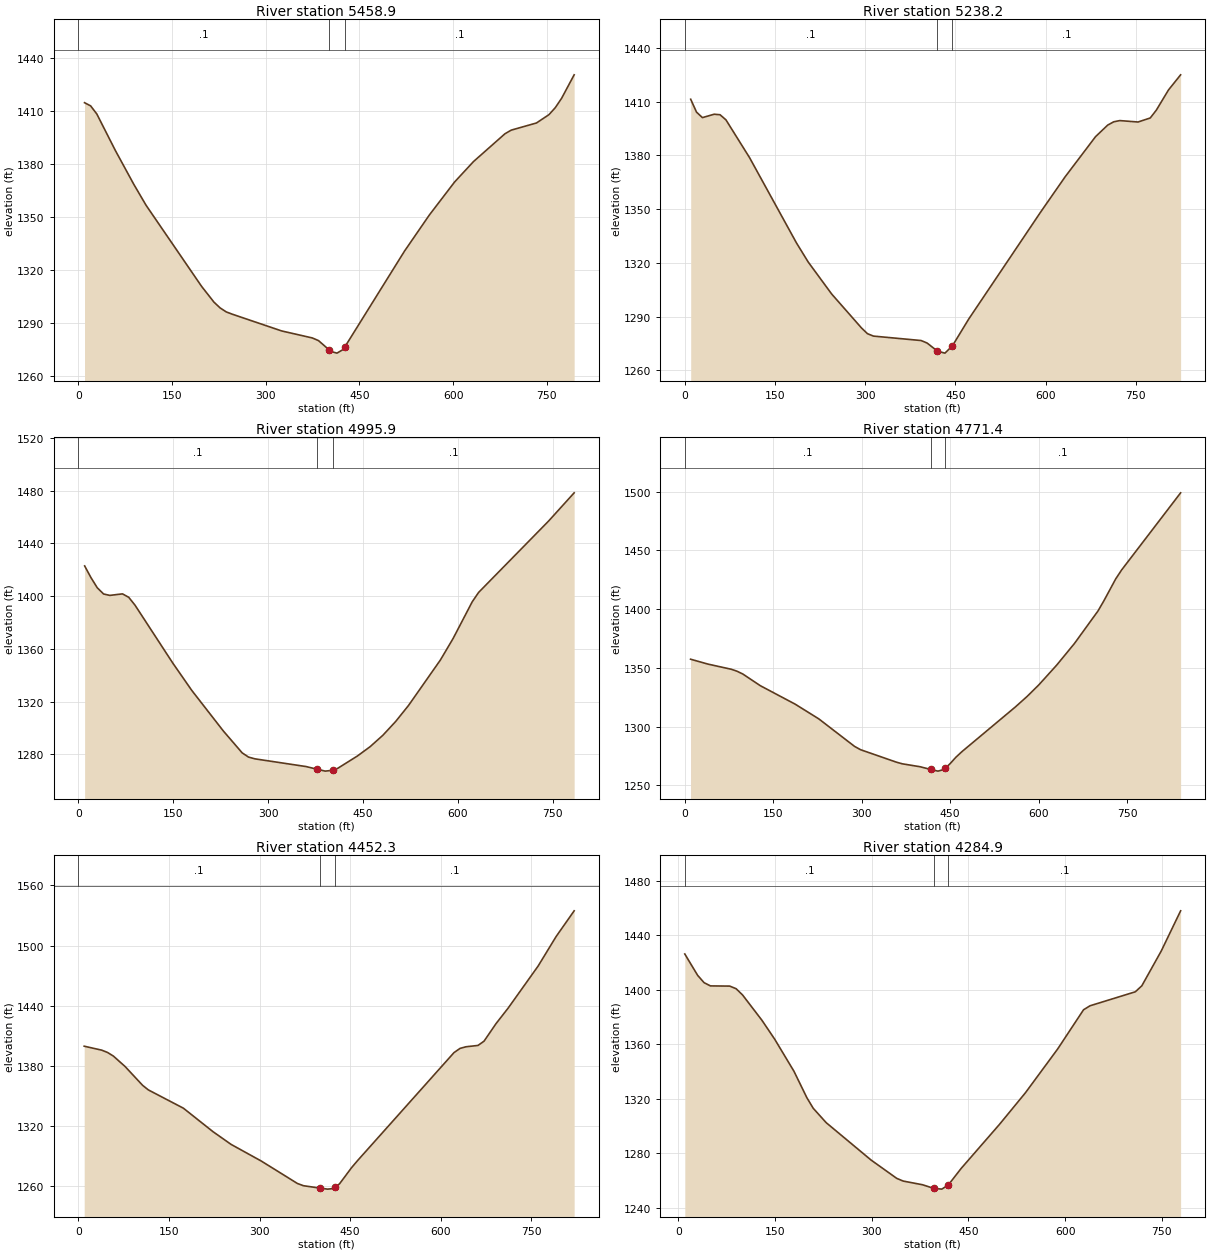
Type RM Length L Ch R = 1 ,5458.9  ,225.1,220.7,216.4
XS GIS Cut Line= 4
     1776713.167      180512.291      1776514.63      180306.261
     1776316.092      180145.183     1776098.825      180017.819
#Sta/Elev= 30
     9.9 1414.87    19.7 1413.06    29.6 1408.47    59.2 1387.85    88.8 1368.63
   108.5 1356.74   197.3 1310.85   217.1 1301.92   226.9 1298.67   236.8 1296.38
   246.7 1295.06   325.5 1285.61   374.6 1281.64   384.5 1280.12   401.5 1274.87
   404.1 1274.01     414 1273.05   423.8 1275.09   426.5 1276.52   522.1 1330.84
   561.9  1351.3   602.2 1369.95   632.4  1381.5   682.8 1397.26   692.9 1399.33
   733.2 1403.37   753.3  1408.1   763.4 1412.06   773.5 1417.35   793.6 1430.65
#Mann= 3 , 0 , 0
       0      .1       0   401.5    .045       0   426.5      .1       0
Bank Sta=401.5,426.5
XS Rating Curve= 0 ,0
Exp/Cntr=0.3,0.1

Type RM Length L Ch R = 1 ,5238.2  ,243.7,242.2,240.7
XS GIS Cut Line= 4
     1776883.173      180324.266     1776713.167      180148.929
     1776447.202      179995.343     1776224.297      179837.807
#Sta/Elev= 30
     9.8 1411.35    19.5 1404.16    29.3  1401.1    48.8 1402.99    58.6 1402.71
    68.4 1399.85   107.5 1378.84   185.6 1331.16   205.1  1320.5   244.2  1302.6
   293.8 1283.64   303.7 1280.46   313.6 1279.11   392.8 1276.63   402.7 1275.27
     420 1270.72   432.5  1269.6     445 1273.71   472.1 1288.67   591.8 1348.47
   632.2    1368   682.8 1390.44     703  1396.9   713.1 1398.76   723.2 1399.44
   753.5 1398.65   773.8  1400.9   783.9 1405.26   804.1 1416.53   824.3 1424.99
#Mann= 3 , 0 , 0
       0      .1       0     420    .045       0     445      .1       0
Bank Sta=420,445
XS Rating Curve= 0 ,0
Exp/Cntr=0.3,0.1

Type RM Length L Ch R = 1 ,4995.9  ,230.1,224.6,219
XS GIS Cut Line= 4
     1776997.863      180074.009     1776788.087       179905.44
     1776544.598      179781.822     1776312.346      179714.394
#Sta/Elev= 30
      10 1422.96    19.9 1414.15    29.9  1406.4    39.9 1401.65    49.8 1400.58
    69.8 1401.74    79.7 1399.13    89.7 1393.12   149.5 1349.08   179.4 1328.41
   229.2 1297.66   259.1 1280.98   269.1 1277.79   279.2 1276.45   360.1 1270.59
     378 1268.51   390.5 1267.12     403 1267.81   410.7 1269.41     441 1278.52
   461.3 1285.65   481.5 1294.33   501.7 1304.79     522 1316.92   572.4 1351.44
   592.6 1367.86   622.8 1395.69   632.9 1402.82   743.7  1457.1     784 1478.48
#Mann= 3 , 0 , 0
       0      .1       0     378    .045       0     403      .1       0
Bank Sta=378,403
XS Rating Curve= 0 ,0
Exp/Cntr=0.3,0.1

Type RM Length L Ch R = 1 ,4771.4  ,323.4,319.1,314.7
XS GIS Cut Line= 4
     1777137.853      179819.787     1776979.133      179703.156
     1776638.248      179609.506     1776348.061      179602.957
#Sta/Elev= 30
     9.8 1357.31    39.4 1353.13    78.8 1348.75    88.6 1347.07    98.5 1344.66
     128 1334.77   187.1 1319.04   227.3 1306.47   287.9 1283.04     298 1280.25
   358.6 1269.66   368.7 1268.24     399 1265.73   416.8 1263.43   429.3    1262
   439.4 1263.39   441.8 1264.53   449.5 1268.18   459.6 1273.79   469.7 1278.51
   560.5 1316.65   580.5 1325.64   600.5 1335.57   630.6  1352.3   660.6 1370.65
   700.6 1398.39   710.6 1407.05   730.6 1425.66   740.7 1433.35   840.7    1499
#Mann= 3 , 0 , 0
       0      .1       0   416.8    .045       0   441.8      .1       0
Bank Sta=416.8,441.8
XS Rating Curve= 0 ,0
Exp/Cntr=0.3,0.1

Type RM Length L Ch R = 1 ,4452.3  ,168.2,167.4,166.6
XS GIS Cut Line= 4
     1777230.959      179409.133     1777035.323      179354.779
     1776698.184      179317.319     1776423.427      179271.789
#Sta/Elev= 30
     9.7 1399.62    38.7 1395.68    48.3 1393.38      58 1389.77    77.4 1379.36
   106.4 1360.58     116 1355.98     174 1337.74     223 1314.31   252.9 1301.64
   302.8 1285.06   362.7 1262.65   372.7 1260.42   400.1 1258.03   412.6 1257.02
   422.5 1257.56   425.1 1258.82   432.5 1262.41   452.5 1278.56   462.4 1285.58
   621.8 1393.17   631.8  1397.4   641.7 1399.04   661.6 1400.38   671.6 1404.63
   691.5 1422.17   711.4 1437.53   761.1 1479.53   790.9 1508.99   820.8 1534.68
#Mann= 3 , 0 , 0
       0      .1       0   400.1    .045       0   425.1      .1       0
Bank Sta=400.1,425.1
XS Rating Curve= 0 ,0
Exp/Cntr=0.3,0.1

Type RM Length L Ch R = 1 ,4284.9  ,201.4,200.9,200.5
XS GIS Cut Line= 4
     1777245.099      179238.653     1776952.911      179174.971
     1776724.405      179156.241     1776473.424      179152.495
#Sta/Elev= 30
      10 1426.13    29.9 1410.48    39.9 1405.08    49.8  1402.7    79.7 1402.56
    89.7 1400.62    99.7 1396.01   129.6 1377.53   149.5 1363.57   179.4 1340.02
   199.4 1320.63   209.3 1312.85   229.3 1302.35     299 1274.88   338.9 1261.41
   348.9 1259.44   378.8 1256.75   396.2 1254.09   408.7 1253.53   418.7 1256.49
   438.6 1268.61   498.4 1301.14   538.4 1324.19   588.6 1356.45   628.7 1385.19
   638.8 1388.12     709 1398.37   719.1 1402.77   749.2 1428.28   779.3 1457.81
#Mann= 3 , 0 , 0
      10      .1       0   396.2    .045       0   418.7      .1       0
Bank Sta=396.2,418.7
XS Rating Curve= 0 ,0
Exp/Cntr=0.3,0.1

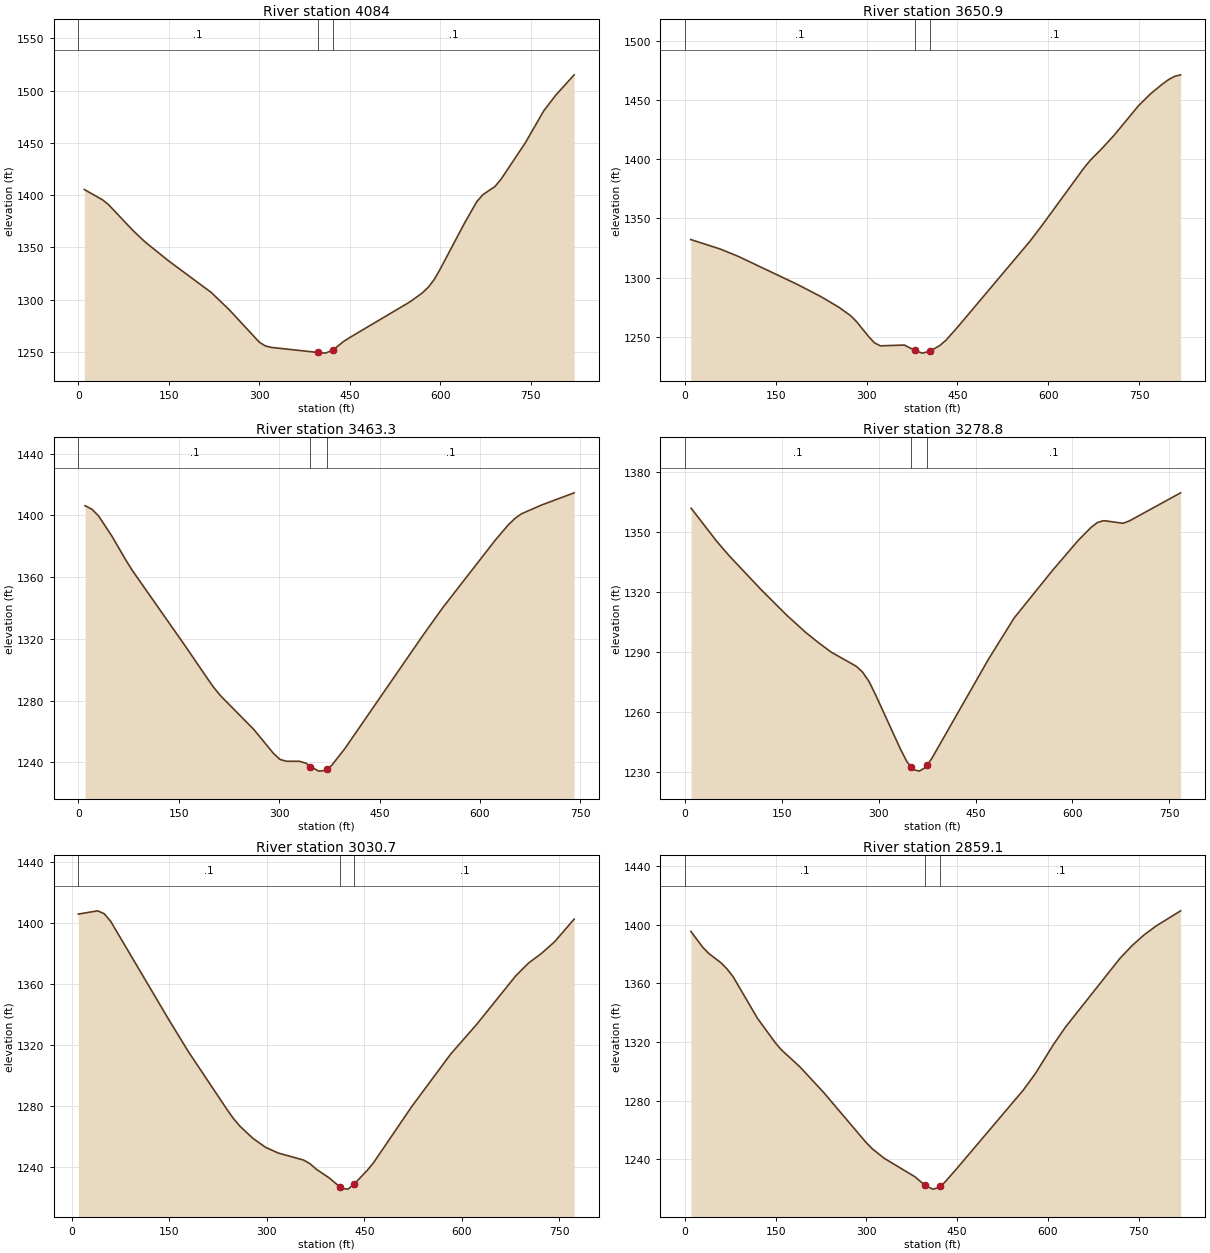
Type RM Length L Ch R = 1 ,4084    ,438.9,433.1,427.3
XS GIS Cut Line= 4
     1777281.547      179004.964     1777072.783      178980.179
     1776784.341      178961.449      1776472.07       178880.43
#Sta/Elev= 30
      10 1405.38      40 1395.61    50.1 1390.93    90.1 1366.47   110.1  1355.5
   150.2 1336.88   220.2 1306.98   250.1 1290.43   299.9 1259.41   309.9 1255.77
   319.9 1254.33   397.1  1249.5   409.6 1248.86   422.1 1251.78   439.5 1259.95
   449.4  1263.6   549.7 1297.92   569.8 1306.27   579.9 1311.78     590 1319.29
   600.1 1329.55   640.4 1373.51   660.6 1393.92   670.7 1400.52   690.8 1408.39
   700.9 1415.44   741.2 1450.32   771.5 1480.71   791.6 1495.85   821.9 1515.16
#Mann= 3 , 0 , 0
       0      .1       0   397.1    .045       0   422.1      .1       0
Bank Sta=397.1,422.1
XS Rating Curve= 0 ,0
Exp/Cntr=0.3,0.1

Type RM Length L Ch R = 1 ,3650.9  ,200.9,187.6,174.3
XS GIS Cut Line= 4
     1777301.288      178523.168     1777096.267      178521.164
     1776784.341      178564.374      1776497.06      178645.648
#Sta/Elev= 30
     9.8 1332.12    58.6 1324.09    87.9 1317.99   185.5 1294.35   224.7 1283.96
   254.2 1275.06   273.9 1267.79   283.8 1262.73   303.4 1250.31   313.3  1244.9
   323.1 1242.44   362.5 1243.12   379.5 1238.62     392  1236.3   404.5 1237.86
   421.5  1242.9   431.4 1247.33   451.1 1258.69   569.7 1330.64   589.6 1343.98
   659.3 1392.72   669.2 1398.89   689.1 1409.15     709 1420.26   748.8 1444.89
   768.7 1454.98   788.6 1463.32   798.6 1467.02   808.5 1469.72   818.5 1471.05
#Mann= 3 , 0 , 0
       0      .1       0   379.5    .045       0   404.5      .1       0
Bank Sta=379.5,404.5
XS Rating Curve= 0 ,0
Exp/Cntr=0.3,0.1

Type RM Length L Ch R = 1 ,3463.3  ,189.7,184.6,179.4
XS GIS Cut Line= 4
     1777173.925      178253.457     1776919.197      178317.138
     1776761.865      178429.518     1776507.138      178556.882
#Sta/Elev= 30
    10.1  1406.3    20.2 1404.07    30.3 1399.67    50.5 1386.35    70.7 1371.27
    80.8 1364.28   161.6 1314.23   191.9 1294.92     202  1288.7   212.1 1283.31
   262.6 1261.07   291.6 1245.74   301.2 1241.87   310.9 1240.68   330.2 1240.66
   339.9 1239.47   346.7 1237.27   359.2 1234.28   368.9 1234.69   371.7 1235.66
   378.6 1238.05   397.9 1248.73   514.8 1322.28   544.3 1340.17   622.9 1384.03
   642.5    1394   652.3 1398.07   662.1  1401.1   691.6  1406.7   740.7 1414.67
#Mann= 3 , 0 , 0
       0      .1       0   346.7    .045       0   371.7      .1       0
Bank Sta=346.7,371.7
XS Rating Curve= 0 ,0
Exp/Cntr=0.3,0.1

Type RM Length L Ch R = 1 ,3278.8  ,248.5,248,247.6
XS GIS Cut Line= 4
     1776990.371      178017.459     1776803.071      178144.823
     1776634.502      178320.884      1776400.64      178504.133
#Sta/Elev= 30
     9.8 1361.84    49.2 1345.38    68.9 1337.98   118.2 1321.11   157.6  1308.4
   187.1 1299.76   206.8 1294.66   226.5 1289.92   265.5  1282.8   275.3 1279.85
     285 1275.27   294.8 1268.91   333.8 1241.42   343.5 1235.32   350.5 1232.38
   353.3  1231.2     363 1230.42   372.8 1232.33   375.5  1233.6   382.5 1236.89
   470.2 1286.46   509.9 1307.03   569.3 1330.81   608.9 1345.74   628.7 1352.21
   638.6 1354.69   648.5 1355.61   678.2  1354.3   688.1 1355.48   767.4 1369.52
#Mann= 3 , 0 , 0
       0      .1       0   350.5    .045       0   375.5      .1       0
Bank Sta=350.5,375.5
XS Rating Curve= 0 ,0
Exp/Cntr=0.3,0.1

Type RM Length L Ch R = 1 ,3030.7  ,165.5,171.6,177.7
XS GIS Cut Line= 4
     1776863.007      177822.667     1776612.026      177983.745
     1776465.932      178141.077     1776241.172      178272.186
#Sta/Elev= 30
     9.9 1405.86    39.8    1408    49.7  1406.1    59.6 1401.18   149.1 1336.62
   178.9 1315.84   238.6 1277.72   248.5 1271.76   258.5 1266.72   278.3 1258.76
   298.2 1252.74   317.7 1249.01   356.8 1244.38   366.5 1242.01   376.3 1238.38
   395.8 1232.76   412.6 1226.78   415.3 1225.77   425.1 1225.33   434.9 1228.82
   454.4 1237.57   464.1 1242.54   522.9 1279.41     583 1313.96     623 1333.45
   683.1 1365.28   703.1 1373.78   723.1 1380.16   743.1 1387.74   773.1 1402.56
#Mann= 3 , 0 , 0
     9.9      .1       0   412.6    .045       0   434.9      .1       0
Bank Sta=412.6,434.9
XS Rating Curve= 0 ,0
Exp/Cntr=0.3,0.1

Type RM Length L Ch R = 1 ,2859.1  ,207.6,207.2,206.9
XS GIS Cut Line= 3
      1776761.44      177704.762     1776423.909      177936.632
     1776086.379      178168.502
#Sta/Elev= 30
      10 1395.48      30 1384.45      40 1380.27    59.9 1374.02    69.9  1369.8
    79.9  1364.5   119.9 1336.28   149.8 1319.35   159.8  1314.6   189.8 1303.24
   229.7 1285.47   299.6 1251.45   309.6 1247.26   329.6 1240.67   379.5  1228.3
     397  1222.3   409.5 1219.71   419.5  1220.7     422 1221.63   429.5 1224.41
   449.5 1233.82   559.3 1287.34   579.3 1298.65   609.3 1318.54   629.2 1330.42
   719.1 1377.24   739.1 1385.88   759.1 1393.22     779 1399.28     819 1409.49
#Mann= 3 , 0 , 0
       0      .1       0     397    .045       0     422      .1       0
Bank Sta=397,422
XS Rating Curve= 0 ,0
Exp/Cntr=0.3,0.1

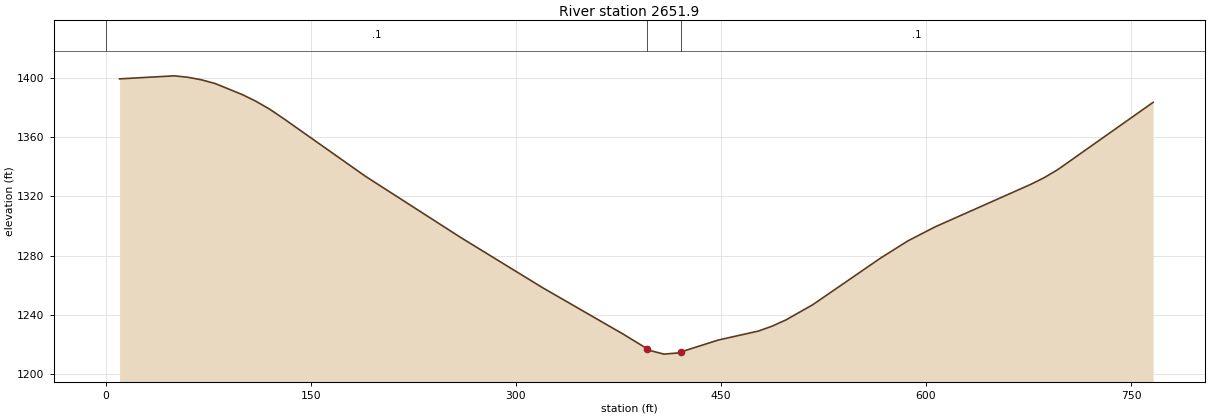
Type RM Length L Ch R = 1 ,2651.9  ,194.8,196.5,198.3
XS GIS Cut Line= 4
      1776664.47      177601.654      1776402.25       177699.05
     1776199.966      177841.397     1775997.683      177968.761
#Sta/Elev= 30
      10  1399.3      50 1401.36    59.9 1400.39    69.9 1398.67    79.9 1396.18
    99.9 1388.65   109.9 1384.12   119.9 1378.78   129.9 1372.56   189.8 1333.57
   259.7 1292.12   319.3 1258.39   378.7  1226.8   395.8 1217.16   398.5 1215.76
   408.3 1213.42   418.2  1214.2   420.8 1214.94   447.9  1222.9   477.6 1229.05
   487.5 1232.35   497.4 1236.46   517.2 1246.83   566.9 1278.37   586.8 1289.92
   606.8 1299.43   676.5 1328.01   686.4 1332.55   696.4 1338.03   766.1 1383.42
#Mann= 3 , 0 , 0
       0      .1       0   395.8    .045       0   420.8      .1       0
Bank Sta=395.8,420.8
XS Rating Curve= 0 ,0
Exp/Cntr=0.3,0.1