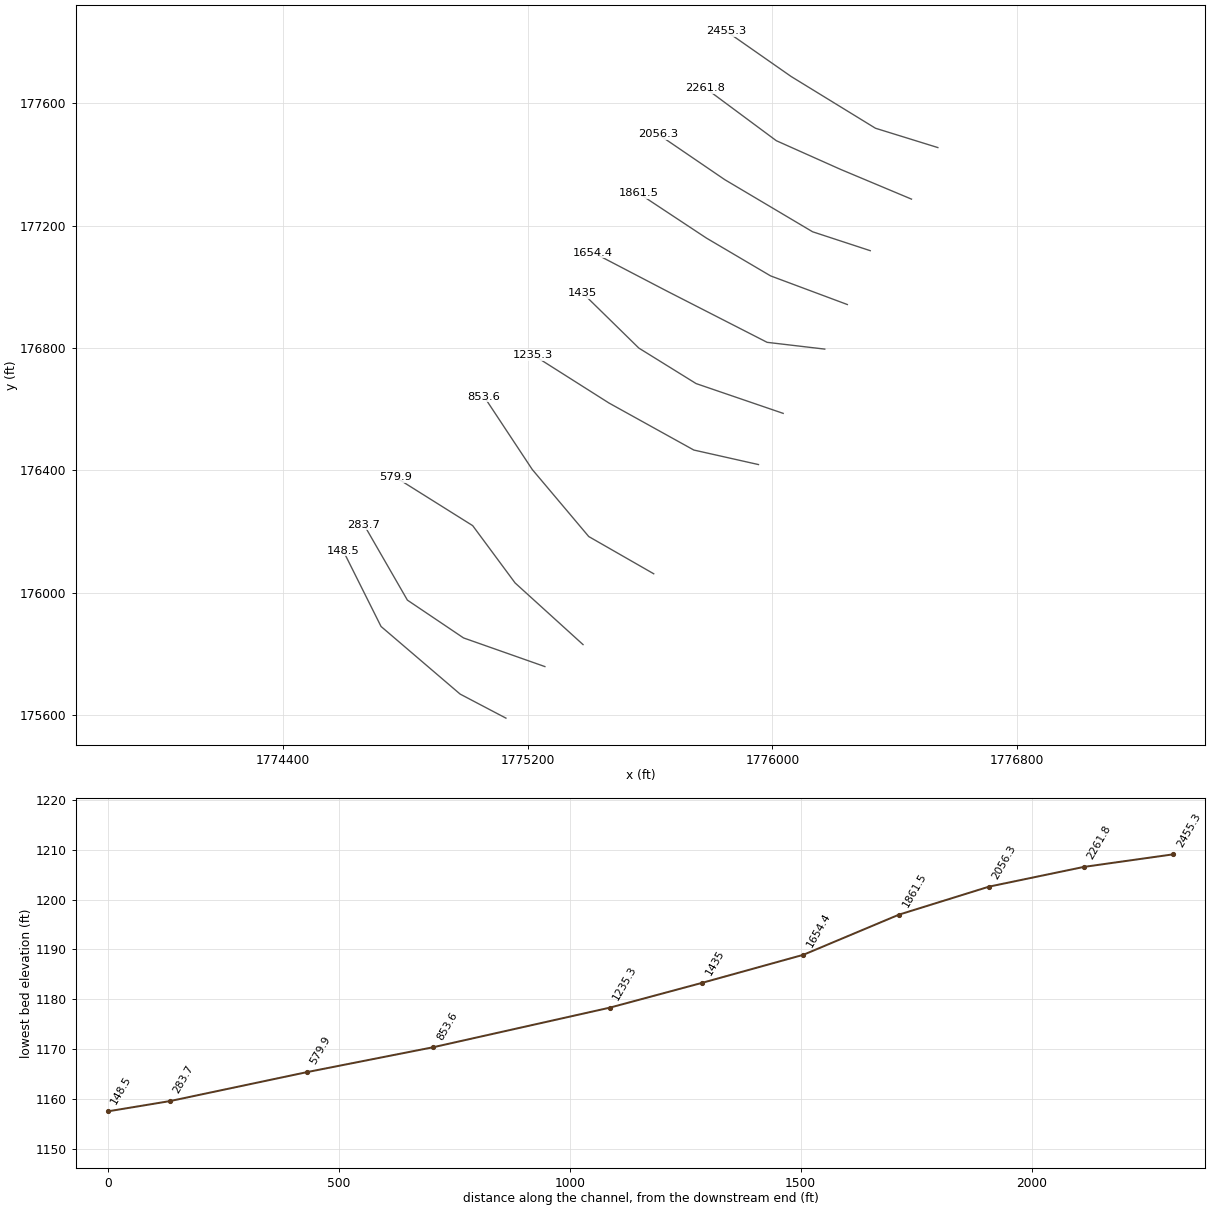
HEC-RAS study Twin Branch.prj: Twin Branch

--- Twin Branch.g01 (geometry) --- (continued)

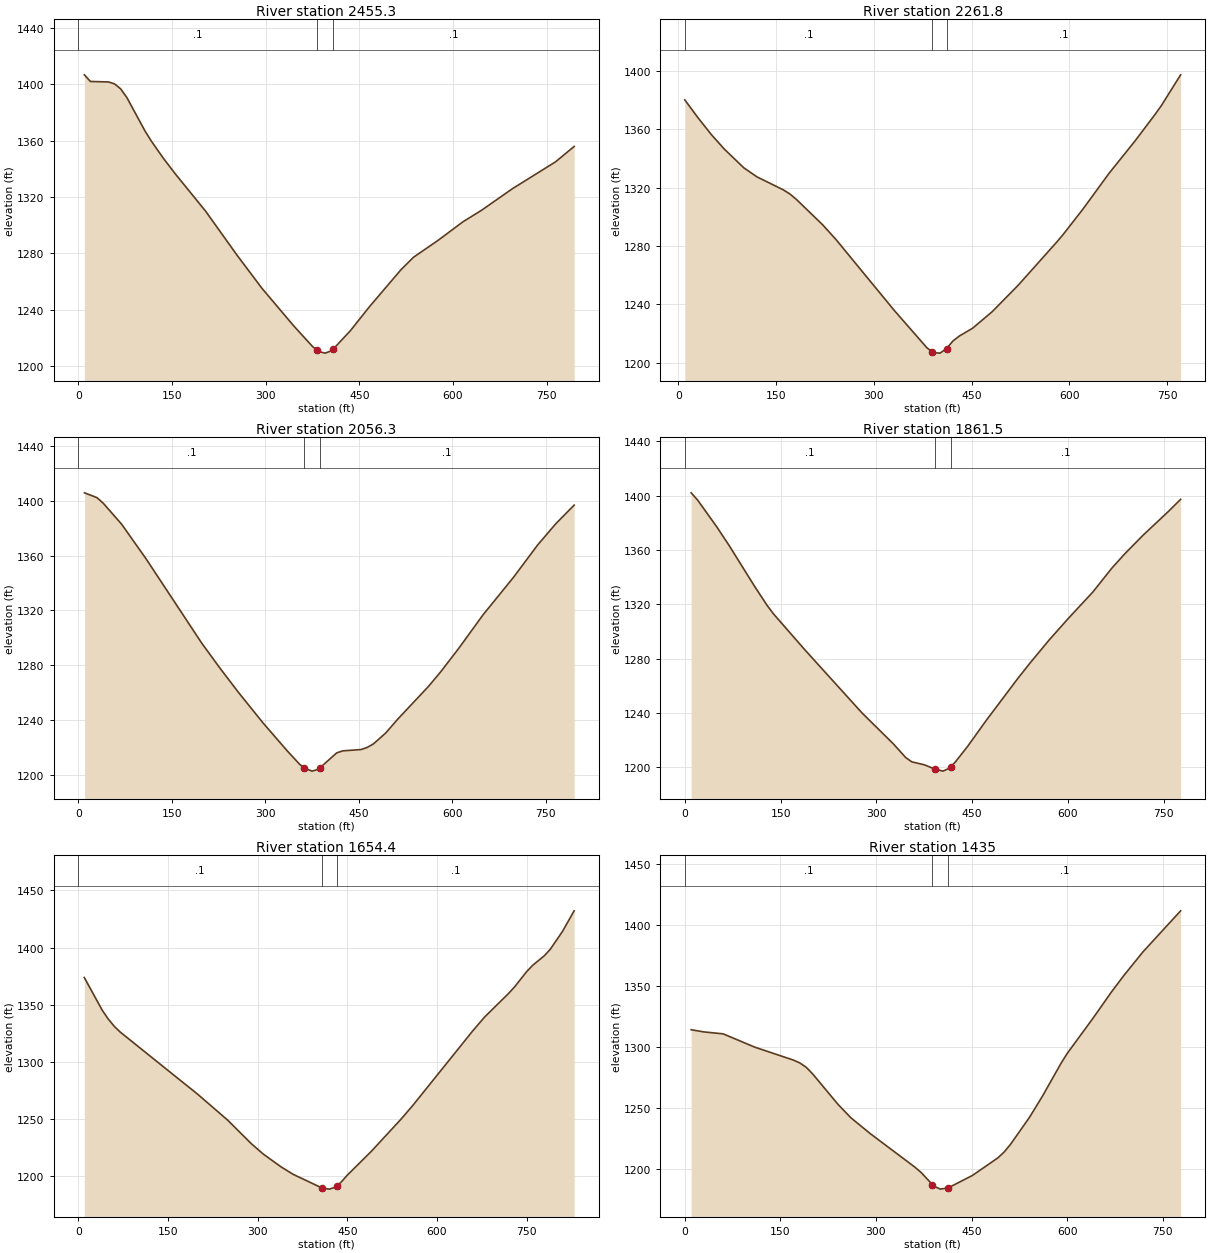
Type RM Length L Ch R = 1 ,2455.3  ,189.9,193.6,197.2
XS GIS Cut Line= 4
     1776540.852       177455.56     1776336.903      177518.737
     1776061.365      177687.812     1775850.394      177835.136
#Sta/Elev= 30
     9.7 1406.63    19.4 1401.91    48.5 1401.58    58.2 1400.15    67.9 1396.61
    77.6  1390.6   106.8 1366.76   116.5 1359.87   135.9 1347.56   155.3 1336.31
   203.8 1309.86   253.9 1278.76   294.3 1254.96   344.8 1228.48   375.1 1213.76
   382.9 1210.98   385.3 1210.13   395.4 1209.05   405.5 1210.73   407.9 1211.75
   435.8 1225.01   466.1 1241.92   516.6  1268.2   536.8 1277.11   576.4 1289.19
     616 1302.29   645.7 1310.44   695.1 1325.75   764.4 1344.89   794.1  1355.8
#Mann= 3 , 0 , 0
       0      .1       0   382.9    .045       0   407.9      .1       0
Bank Sta=382.9,407.9
XS Rating Curve= 0 ,0
Exp/Cntr=0.3,0.1

Type RM Length L Ch R = 1 ,2261.8  ,208.7,205.4,202.2
XS GIS Cut Line= 4
     1776454.694       177286.99     1776222.442      177384.386
     1776012.667      177478.036     1775780.415      177650.352
#Sta/Elev= 30
    10.1 1380.07    30.2 1367.93    50.4 1356.53    70.5 1346.45   100.7 1333.51
   120.9  1327.3   161.2 1318.44   171.3 1315.61   181.3 1311.89   221.6 1294.48
   241.8 1284.52   331.8 1235.62   381.7 1210.13   389.2 1207.64   391.7 1206.82
   401.7 1206.53   411.7 1209.69   421.6 1214.89   431.6 1218.34   451.6 1223.58
   481.6 1234.88   521.5 1253.02   581.3 1282.91   591.3 1288.23   621.2 1305.38
   661.1 1329.82     701 1352.02   730.9 1369.71   740.9  1375.9   770.8 1397.25
#Mann= 3 , 0 , 0
    10.1      .1       0   389.2    .045       0   411.7      .1       0
Bank Sta=389.2,411.7
XS Rating Curve= 0 ,0
Exp/Cntr=0.3,0.1

Type RM Length L Ch R = 1 ,2056.3  ,194.7,194.8,194.9
XS GIS Cut Line= 4
     1776319.838      177118.421     1776131.349      177180.219
     1775844.097      177350.672     1775626.672      177498.962
#Sta/Elev= 30
     9.9 1405.92    29.8 1402.42    39.7 1398.46    69.4 1383.05   109.1 1357.43
   198.4 1295.83   227.8 1277.51   257.3  1259.9   296.6 1237.69   335.9 1217.03
   355.5 1207.42   362.7 1204.77   375.2 1202.58     385  1203.9   387.7 1204.97
   414.5  1215.9   424.3 1217.39   453.8 1218.35   463.6 1219.91   473.4 1222.43
   493.1 1230.37   512.7 1240.65   561.6 1264.36   581.1 1274.93   610.4 1292.27
   649.3 1316.72   698.1  1344.1   737.1 1367.86   766.3 1383.42   795.6 1396.95
#Mann= 3 , 0 , 0
       0      .1       0   362.7    .045       0   387.7      .1       0
Bank Sta=362.7,387.7
XS Rating Curve= 0 ,0
Exp/Cntr=0.3,0.1

Type RM Length L Ch R = 1 ,1861.5  ,205.5,207.1,208.8
XS GIS Cut Line= 4
     1776244.918      176942.359     1775993.937      177036.009
     1775784.161      177159.627     1775563.148       177305.72
#Sta/Elev= 30
     9.9 1402.15    19.8    1397    49.6 1377.37    69.5 1363.26   109.1 1333.34
     129  1319.1   138.9 1312.89   188.5 1286.15   277.6 1239.82   326.3 1217.21
   345.8 1207.03   355.5 1203.81     375 1201.64   391.7 1198.48   404.2 1196.98
     414 1199.08   416.7 1200.38   423.7 1203.77   443.2 1215.48   472.4 1234.65
   521.2 1265.17   540.8 1276.81   570.2 1293.51   599.7 1309.16   638.9 1329.03
   668.4  1346.5     688 1356.75   717.4 1370.86   756.7 1388.21   776.3 1397.36
#Mann= 3 , 0 , 0
       0      .1       0   391.7    .045       0   416.7      .1       0
Bank Sta=391.7,416.7
XS Rating Curve= 0 ,0
Exp/Cntr=0.3,0.1

Type RM Length L Ch R = 1 ,1654.4  ,221.7,219.4,217.1
XS GIS Cut Line= 4
     1776171.111      176796.612     1775982.699      176818.741
     1775653.051      176987.311     1775413.946      177112.056
#Sta/Elev= 30
      10 1373.83    39.9 1345.35    49.9 1337.67    59.9 1331.35    69.9 1326.26
   199.7 1271.85   249.7 1249.32   289.8 1228.48   309.8 1219.43   339.8 1208.18
   359.8 1201.77   407.4    1190   419.9 1188.94   429.9 1190.56   432.4  1191.7
   439.9 1195.14   449.9 1201.08   489.9 1221.79   539.9 1250.05     560  1262.3
   659.8 1327.15   679.8 1339.32   719.8 1359.89   729.8 1365.59   749.7 1378.71
   759.7 1384.29   779.7 1392.89   789.7 1398.56   809.7 1413.83   829.6 1432.12
#Mann= 3 , 0 , 0
       0      .1       0   407.4    .045       0   432.4      .1       0
Bank Sta=407.4,432.4
XS Rating Curve= 0 ,0
Exp/Cntr=0.3,0.1

Type RM Length L Ch R = 1 ,1435    ,198.3,199.6,201
XS GIS Cut Line= 4
     1776035.143      176586.489     1775750.447      176683.885
     1775563.148      176800.011     1775379.594      176979.819
#Sta/Elev= 30
      10 1314.16    30.1 1312.36    60.2 1310.77   110.3 1299.76   170.5 1289.24
   180.5  1286.9   190.6 1283.35   200.6 1277.94   240.7 1252.76   260.8 1241.84
   290.9 1228.94     361 1201.43     371 1196.94   388.6 1187.07     391 1185.74
   401.1 1183.32   413.6 1184.41   451.2 1194.48   491.2 1208.91   501.2 1213.74
   511.3 1220.16     541 1242.25   560.8 1259.14   590.5  1286.6   600.3 1294.78
   639.9 1323.02   669.5 1345.06   689.3 1358.79   718.9 1377.94   778.2 1411.76
#Mann= 3 , 0 , 0
       0      .1       0   388.6    .045       0   413.6      .1       0
Bank Sta=388.6,413.6
XS Rating Curve= 0 ,0
Exp/Cntr=0.3,0.1

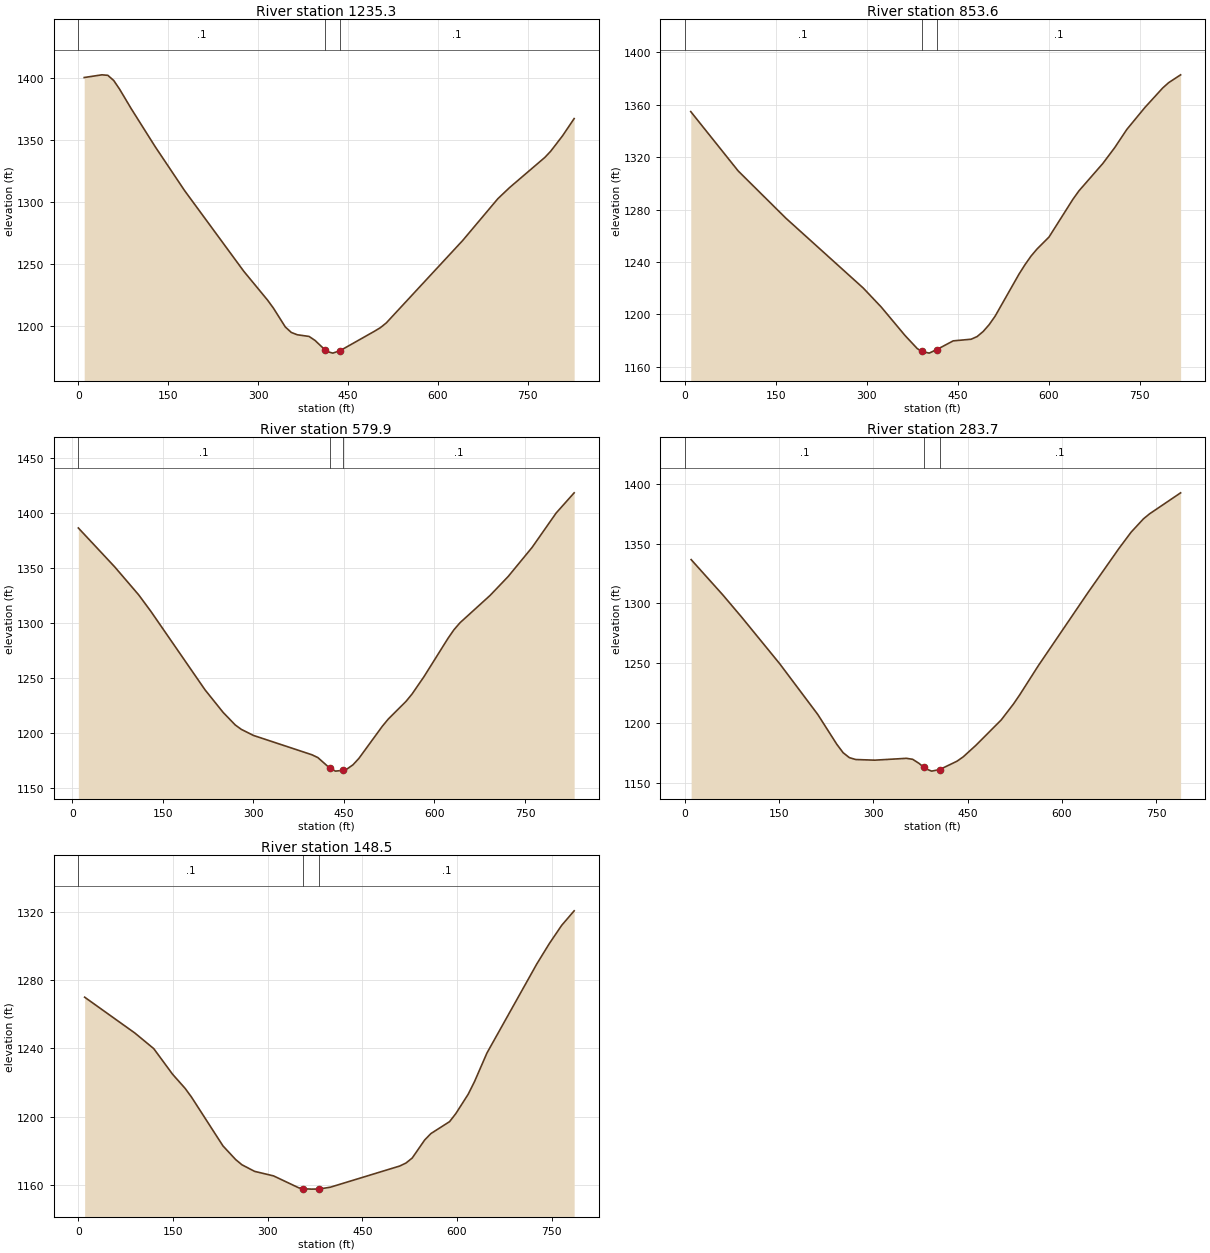
Type RM Length L Ch R = 1 ,1235.3  ,391.8,381.7,371.7
XS GIS Cut Line= 4
     1775954.344      176419.128     1775742.955      176466.618
     1775465.752      176620.203     1775217.677      176777.432
#Sta/Elev= 30
     9.8 1400.45    39.4 1402.62    49.2 1402.22    59.1 1398.04    68.9 1391.01
    88.6 1375.07     128 1344.89   177.3 1309.33   276.1 1244.29   315.7 1221.11
   325.6 1214.55   345.4 1199.41   355.3 1195.04   365.2 1193.17     385 1191.81
   394.9 1188.61   412.1 1180.76   414.7  1179.7   424.6 1178.36   437.1 1180.43
     494 1195.96   503.9 1198.85   513.8 1202.68   641.3 1269.12     700 1302.79
   719.6 1311.78   778.3 1336.02   788.1 1341.02   807.7 1353.32   827.3 1367.36
#Mann= 3 , 0 , 0
       0      .1       0   412.1    .045       0   437.1      .1       0
Bank Sta=412.1,437.1
XS Rating Curve= 0 ,0
Exp/Cntr=0.3,0.1

Type RM Length L Ch R = 1 ,853.6   ,275.5,273.7,272
XS GIS Cut Line= 4
     1775611.845       176062.05     1775399.421      176183.753
      1775214.77      176402.936     1775056.987      176641.589
#Sta/Elev= 30
     9.8 1354.69    88.1 1309.39   166.5 1273.45   294.2  1220.1   323.9  1205.6
   363.4 1183.74   383.2 1173.96   390.4  1171.8   402.9 1170.45   415.4 1173.14
   442.5  1179.8   472.1 1181.05     482  1183.1   491.9 1186.93   501.8 1192.16
   511.6  1198.6   551.1 1230.77     561 1237.98   570.9 1244.49   580.7 1249.84
   600.5    1259   639.9  1287.8   649.8  1294.2   689.3 1315.15     709 1327.31
   728.7 1341.02   758.3 1357.67   787.9 1372.68   797.8 1376.77   817.5 1382.74
#Mann= 3 , 0 , 0
       0      .1       0   390.4    .045       0   415.4      .1       0
Bank Sta=390.4,415.4
XS Rating Curve= 0 ,0
Exp/Cntr=0.3,0.1

Type RM Length L Ch R = 1 ,579.9   ,286.8,296.2,305.6
XS GIS Cut Line= 4
     1775380.731      175830.491      1775158.58      176032.082
     1775019.978      176219.382     1774767.209      176377.915
#Sta/Elev= 30
      10  1386.3      70 1351.12     110 1325.53     130  1310.7     220 1239.21
     250 1218.72     270 1207.36     280  1203.4     300  1197.9   397.1 1180.29
   406.8 1177.76   426.2 1168.38   435.9 1165.46   448.4 1166.18   455.3 1167.46
     465  1171.2   474.7 1176.95   513.6  1206.2   523.3 1212.64   552.9 1228.84
   562.8 1235.45   582.7 1251.31   622.5 1286.13   632.4 1293.94   642.4 1300.27
   692.1 1325.02     722 1342.16   761.7 1368.62   801.5 1399.82   831.4 1418.21
#Mann= 3 , 0 , 0
      10      .1       0   426.2    .045       0   448.4      .1       0
Bank Sta=426.2,448.4
XS Rating Curve= 0 ,0
Exp/Cntr=0.3,0.1

Type RM Length L Ch R = 1 ,283.7   ,138.3,135.2,132
XS GIS Cut Line= 4
     1775255.976      175758.625      1774990.01      175852.275
     1774806.457      175975.893     1774664.109      176223.128
#Sta/Elev= 30
    10.1 1336.66    60.4 1307.18    90.6 1288.42   151.1 1249.43   211.5 1207.09
   241.7 1182.19   251.8 1175.09   261.8 1170.94   271.9 1169.38   302.1 1168.84
   352.4 1170.38   362.4 1169.57   372.5 1166.18   380.1 1162.85   382.6 1161.76
   392.6 1159.67   405.1 1160.93   432.9 1167.96   442.9 1171.65     463 1181.27
   503.3 1202.53   522.9 1215.96   532.8  1223.6   562.3 1247.92     641 1308.88
   690.2 1345.77   709.9 1359.67   729.5 1370.79   739.4 1375.04   788.6 1392.55
#Mann= 3 , 0 , 0
       0      .1       0   380.1    .045       0   405.1      .1       0
Bank Sta=380.1,405.1
XS Rating Curve= 0 ,0
Exp/Cntr=0.3,0.1

Type RM Length L Ch R = 1 ,148.5   ,154,148.5,143
XS GIS Cut Line= 4
     1775128.612      175590.055     1774978.772      175668.721
     1774720.299      175889.735     1774596.681       176136.97
#Sta/Elev= 30
      10 1269.91    89.6 1248.93   119.5 1239.81   149.3 1224.84   169.2 1216.56
   179.2 1211.52   229.2 1182.89   249.3  1174.9   259.3 1171.84   279.3    1168
   309.3 1165.35   349.3 1158.37   356.8 1157.84   369.3  1157.6   381.8 1157.68
   399.3 1158.72   509.3 1171.12   519.2 1172.87   529.1 1175.81   548.8 1186.34
   558.7 1190.11   588.3 1197.09   598.2  1201.8   617.9 1213.19   627.8 1220.52
   647.5 1237.24   726.5 1289.35   746.2 1301.19     766 1311.98   785.7 1320.44
#Mann= 3 , 0 , 0
       0      .1       0   356.8    .045       0   381.8      .1       0
Bank Sta=356.8,381.8
XS Rating Curve= 0 ,0
Exp/Cntr=0.3,0.1

Chan Stop Cuts=-1
Use User Specified Reach Order=0